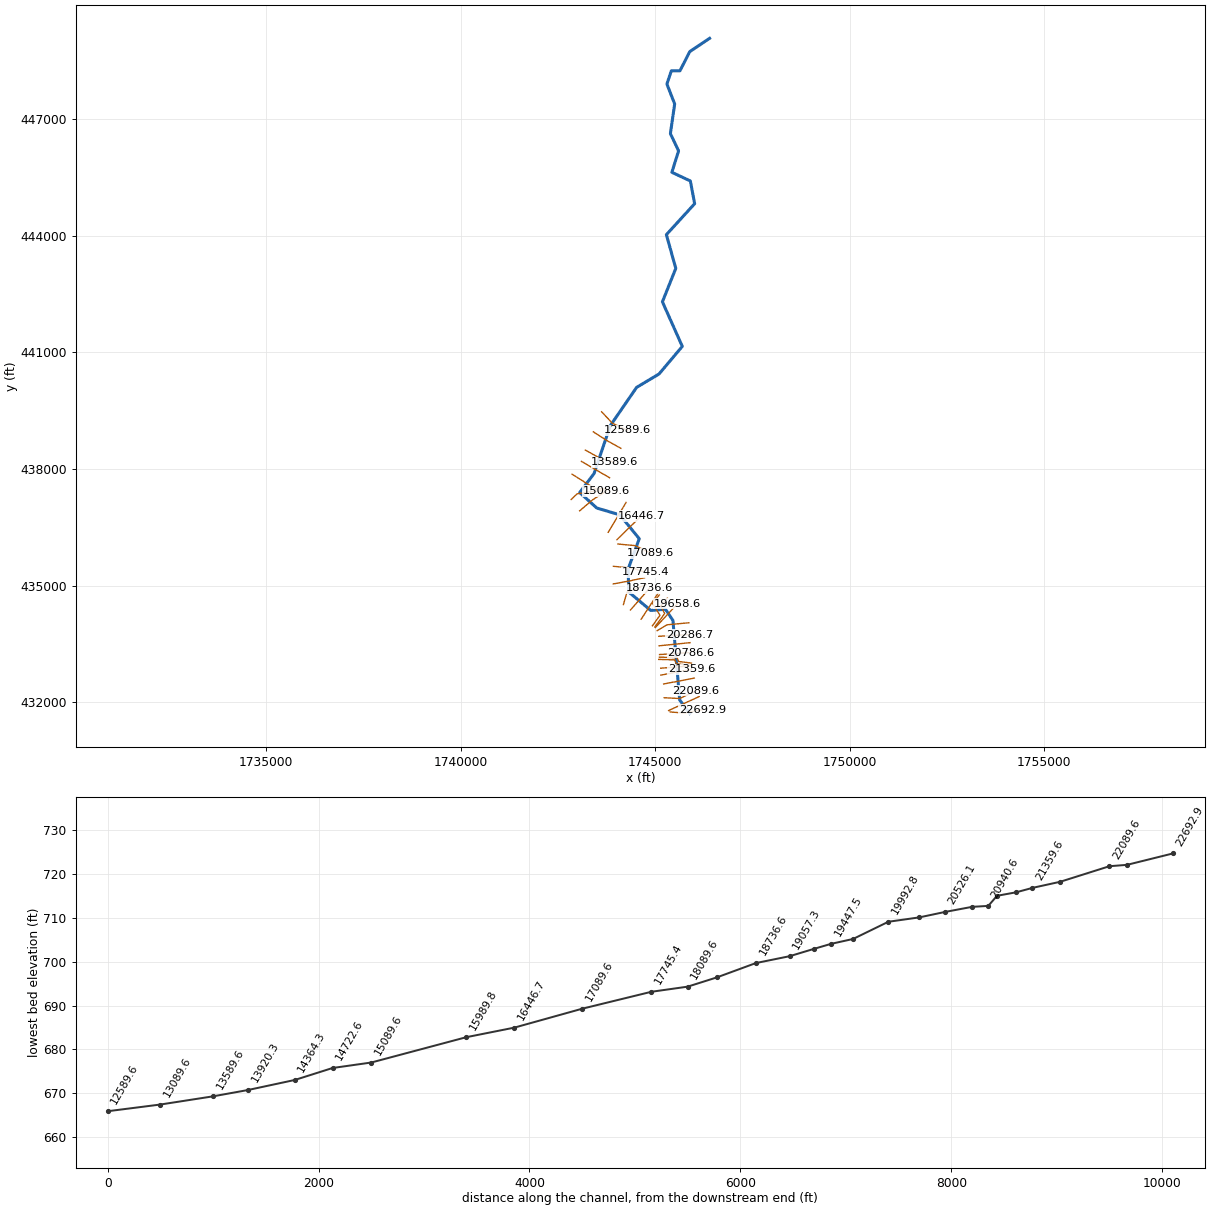
--- FORKCK.prj (project) ---

Proj Title=FORKCK
Current Plan=p01
Default Exp/Contr=0,0
English Units
Geom File=g01
Flow File=f01
Plan File=p01
Background Map Layer=FpSmooth_P100yr
BEGIN DESCRIPTION:
END DESCRIPTION:
DSS Export Rating Curves= 0
DSS Export Rating Curve Sorted= 0
DSS Export Volume Flow Curves= 0
DXF OffsetX= 0
DXF OffsetY= 0
DXF ScaleX= 0
DXF ScaleY= 0

--- FORKCK.p01 (plan) ---

Plan Title=Floodplain
Program Version=4.00
Geom File=g01
Flow File=f01
K Sum by GR=0
Std Step Tol=0.01
Critical Tol=0.01
Num of Std Step Trials=20
Max Error Tol=0.3
Flow Tol Ratio=0.001
Split Flow NTrial=30
Split Flow Tol=0.02
Split Flow Ratio=0.02
Log Output Level=0
Friction Slope Method=1
Unsteady Friction Slope Method=2
Unsteady Bridges Friction Slope Method=1
Global Log Level=0
CheckData=False
Run HTab=0
Run UNet=0
Run PostProcess=0
UNET Theta=0
UNET Theta Warmup=0
UNET ZTol=0
UNET ZSATol=0
UNET MxIter=0
UNET MaxInSteps=0
UNET DtIC=0
UNET DtMin=0
UNET MaxCRTS=0
UNET WFStab=0
UNET SFStab=0
UNET WFX=0
UNET SFX=0
UNET DSS MLevel=0
UNET DZMax Abort=0
UNET Convert EG Bridges=0
UNET Use Existing IB Tables=0
UNET Froude Limit=0
UNET Froude Power=0
Write IC File=0
Echo Input=False
Echo Output=False
Write Detailed=0

--- FORKCK.f01 (steady flow) ---

Flow Title=NFF Regression Equation
Program Version=4.10
Number of Profiles= 1
Profile Names=P100yr
River Rch & RM=FORKCK,Main            ,22692.9
2003.138
River Rch & RM=FORKCK,Main            ,19992.8
2088.763
River Rch & RM=FORKCK,Main            ,12138.4
2291.017
River Rch & RM=FORKCK,Main            ,11740.3
2718.651
River Rch & RM=FORKCK,Main            ,11599.2
2722.278
River Rch & RM=FORKCK,Main            ,9089.6
3021.223
River Rch & RM=FORKCK,Main            ,568.1
3271.278
River Rch & RM=FORKCK,Main            ,128.4
3272.022
Boundary for River Rch & Prof#=FORKCK,Main            , 1
Up Type= 0
Dn Type= 3
Dn Slope=0.00137
DSS Import GetInterval= 0
DSS Import GetPeak= 0
DSS Import FillOption= 0

--- FORKCK.g01 (geometry) ---

Geom Title=USGS 10m DEM
Program Version=5.03

River Reach=FORKCK          ,Main
Reach XY= 30
     1745887.436      431719.087     1745628.755      432063.706
     1745455.144      434108.758     1745263.304      434396.084
     1744883.964      434364.834     1744317.123      434840.528
      1744304.97      435433.324     1744588.824        436209.8
     1744087.956      436822.647      1743496.81      436997.994
     1743057.574      437395.477      1743425.63      437882.369
     1743845.769      439117.525     1744521.116      440098.949
     1745097.505      440443.567     1745696.197      441152.478
     1745184.472      442298.575     1745528.894      443158.147
     1745286.462      444024.446     1746013.759      444820.575
     1745902.898      445404.727     1745427.779      445627.423
     1745600.771       446179.17     1745390.013      446621.396
     1745499.656      447385.119     1745299.862      447897.516
     1745414.378       448236.19     1745634.882       448236.19
     1745888.278      448730.192     1746397.609      449071.453

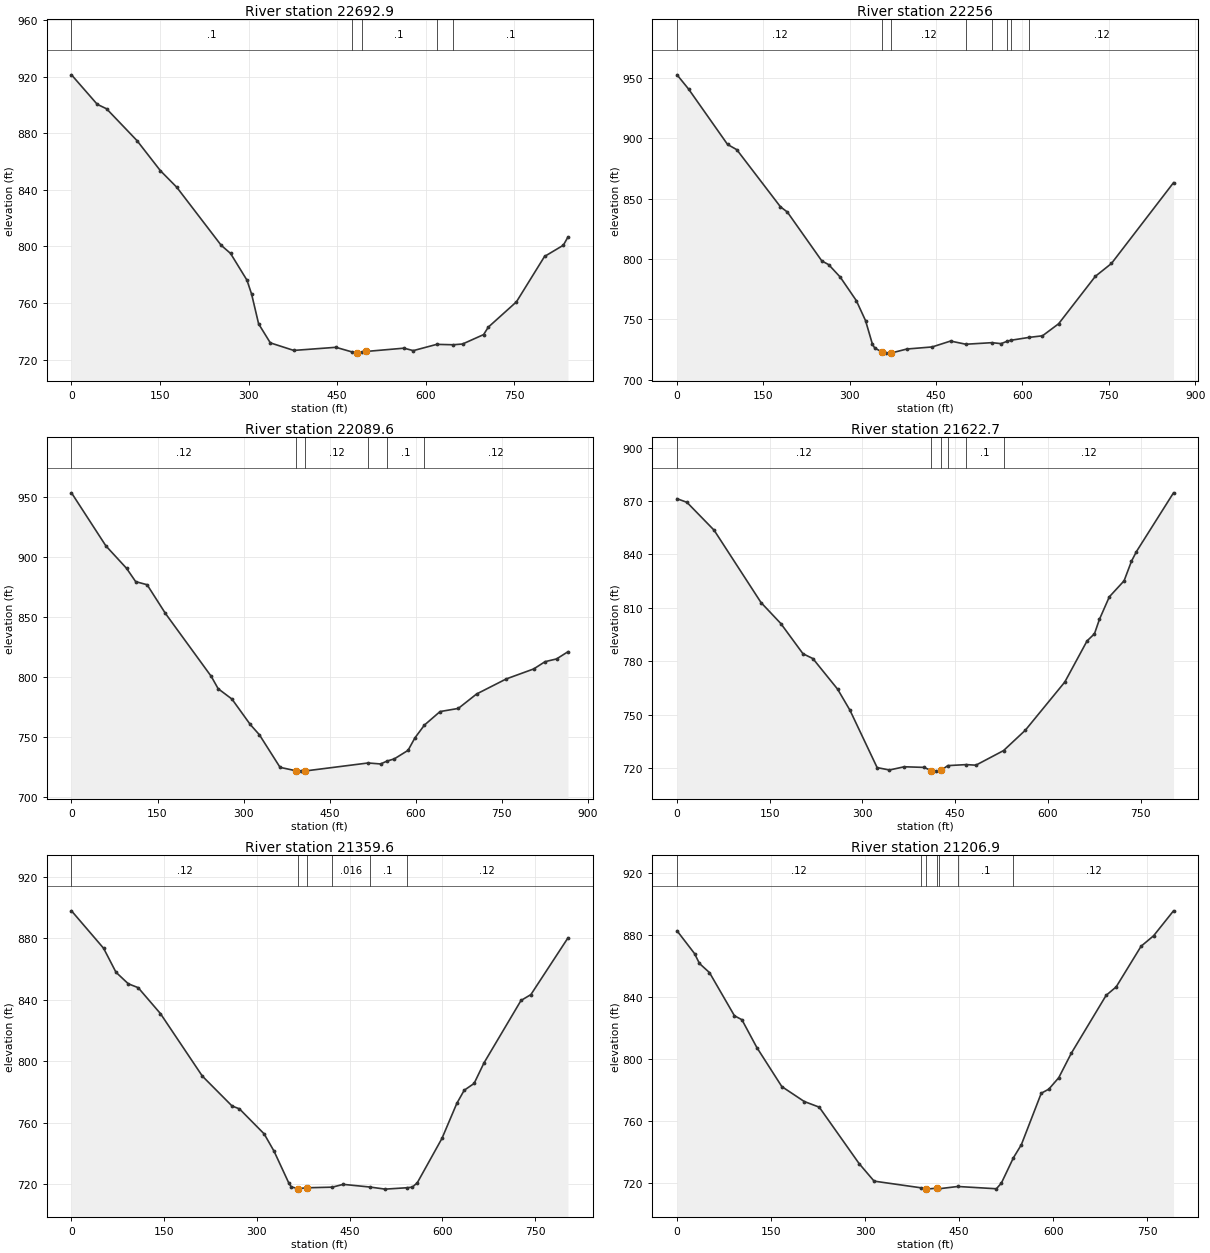
Type RM Length L Ch R = 1 ,22692.9 ,430.9,436.9,441.4
XS GIS Cut Line= 3
     1745383.127      431755.777     1745742.502      431726.263
     1746214.725      431814.805
#Sta/Elev= 30
       0   921.2    43.6  900.39    59.4  897.23     111  874.74   150.6  853.51
   178.3  841.83   253.6  800.82   269.4  795.11   297.2  776.23   305.1  766.37
     317  745.34   336.8  731.94   376.5   726.6   447.9   728.8   475.7  725.47
   483.7  724.69   484.1   724.7   491.6  725.22   499.1  725.87   563.1  728.19
     579  726.46   618.7  730.88   646.5   730.6   662.4  731.12   698.1  737.78
     706  743.02   753.7   760.9   801.3  792.95   833.1  800.87     841   806.7
#Mann= 5 ,-1 , 0
       0      .1       0   475.7    .045       0   491.6      .1       0
   618.7    .013       0   646.5      .1       0
Bank Sta=484.1,499.1
XS Rating Curve= 0 ,0
Exp/Cntr=0.3,0.1

Type RM Length L Ch R = 1 ,22256   ,177.5,166.4,167.9
XS GIS Cut Line= 2
     1745343.734      431792.291     1746128.456       432149.93
#Sta/Elev= 30
       0   952.4      20  940.67    87.8  894.78   103.8  890.45   179.7  843.15
   191.6  838.86   251.5   798.4   263.5  795.28   283.5     785   311.4  765.57
   327.4  749.04   339.4   729.5   343.4  726.31   356.8722.8275   363.3  722.08
   371.8  722.14   399.2  725.48   443.2   727.2   475.1  732.07  501.71729.4431
   546.9730.7335   562.9  729.94  572.93731.8063  579.36732.6707  611.82735.1278
   634.8  736.42   662.8  746.36   726.6  785.64   754.6  796.27   862.4  863.14
#Mann= 8 ,-1 , 0
       0     .12       0   356.8    .045       0   371.8     .12       0
  501.71    .016       0   546.9     .06       0  572.93      .1       0
  579.36     .05       0  611.82     .12       0
Bank Sta=356.8,371.8
XS Rating Curve= 0 ,0
Exp/Cntr=0.3,0.1

Type RM Length L Ch R = 1 ,22089.6 ,461,466.9,460.1
XS GIS Cut Line= 3
       1745230.2      432121.686     1745629.202      432100.958
     1746049.635      432301.792
#Sta/Elev= 30
       0  953.24    59.9  909.16    95.9   890.5   111.9  879.37   131.8  876.81
   163.8   852.9   243.7  800.52   255.7   790.3   279.7  781.72   311.6  760.58
   327.6  751.99   363.6  724.91     392     722   399.5  721.77     407  721.88
  517.04728.5498   538.9  727.73  549.77730.0801   562.8  731.97   586.7  739.06
   598.7  749.43  615.24760.0696   642.5  771.31   674.3  773.92   706.2  785.92
     758  798.48   805.7  806.75   825.6  812.82   845.6  815.09   865.5  821.07
#Mann= 6 ,-1 , 0
       0     .12       0     392    .045       0     407     .12       0
  517.04    .016       0  549.77      .1       0  615.24     .12       0
Bank Sta=392,407
XS Rating Curve= 0 ,0
Exp/Cntr=0.3,0.1

Type RM Length L Ch R = 1 ,21622.7 ,263.2,263.1,263
XS GIS Cut Line= 2
     1745216.318      432474.359      1746005.38        432625.4
#Sta/Elev= 30
       0  871.35      16  869.33      60  853.65   135.9  812.99   167.9   801.2
   203.8  784.21   219.8   781.5   259.8  764.31   279.8  752.47   323.8  720.21
   343.7  718.85   367.7  720.67   399.7  720.32   411.7  718.48   419.7  718.22
   427.7  718.75  438.12721.3154  468.19721.8879   483.6  721.56  528.33729.7545
   563.6  741.21   627.5  768.32   663.5  791.42   675.5  795.43   683.5  803.52
   699.5  816.19   723.4   825.2   735.4  836.23   743.4  841.63   803.4  874.66
#Mann= 6 ,-1 , 0
       0     .12       0   411.7    .045       0   427.7     .12       0
  438.12    .016       0  468.19      .1       0  528.33     .12       0
Bank Sta=411.7,427.7
XS Rating Curve= 0 ,0
Exp/Cntr=0.3,0.1

Type RM Length L Ch R = 1 ,21359.6 ,154.9,152.8,149.6
XS GIS Cut Line= 2
     1745143.401      432700.921     1745932.464      432851.963
#Sta/Elev= 30
       0  897.76      52  873.39      72  857.83    91.9  850.33   107.9  847.81
   143.9  830.97   211.8  790.28   259.8  770.89   271.8  769.01   311.8  752.73
   327.8  741.47   351.7  720.75   355.7  718.27   366.6  717.19   381.6  717.72
  422.14718.1105   439.7  719.93  482.28718.2185   507.6  716.83  542.43  717.72
   551.6  718.13   559.6  720.99   599.5  749.82   623.5  772.55   635.5  781.12
   651.5  785.53   667.5  798.89   727.4  839.48   743.4  843.31   803.4  880.17
#Mann= 6 ,-1 , 0
       0     .12       0   366.6    .045       0   381.6     .12       0
  422.14    .016       0  482.28      .1       0  542.43     .12       0
Bank Sta=366.6,381.6
XS Rating Curve= 0 ,0
Exp/Cntr=0.3,0.1

Type RM Length L Ch R = 1 ,21206.9 ,214.8,183.6,153.6
XS GIS Cut Line= 2
     1745140.871      432880.783     1745930.802      432939.376
#Sta/Elev= 30
       0  882.73    27.9  868.04    35.8  861.62    51.8  855.72    91.6  827.85
   103.5  825.29   127.4  807.28   167.2  782.08     203  772.44   226.9  768.79
   290.6  732.28   314.4     721  388.67716.7131     398  715.83     414  716.46
  418.29716.0859  447.91717.5356   509.5  716.07   517.4  719.68  536.76736.1472
   549.3  744.51   581.1  777.79   593.1  780.42     609  787.82   628.9  803.54
   684.6  841.04   700.6  846.48   740.4  872.78   760.3  879.51   792.1  895.64
#Mann= 7 ,-1 , 0
       0     .12       0  388.67    .016       0     398    .045       0
     414    .016       0  418.29     .05       0  447.91      .1       0
  536.76     .12       0
Bank Sta=398,414
XS Rating Curve= 0 ,0
Exp/Cntr=0.3,0.1

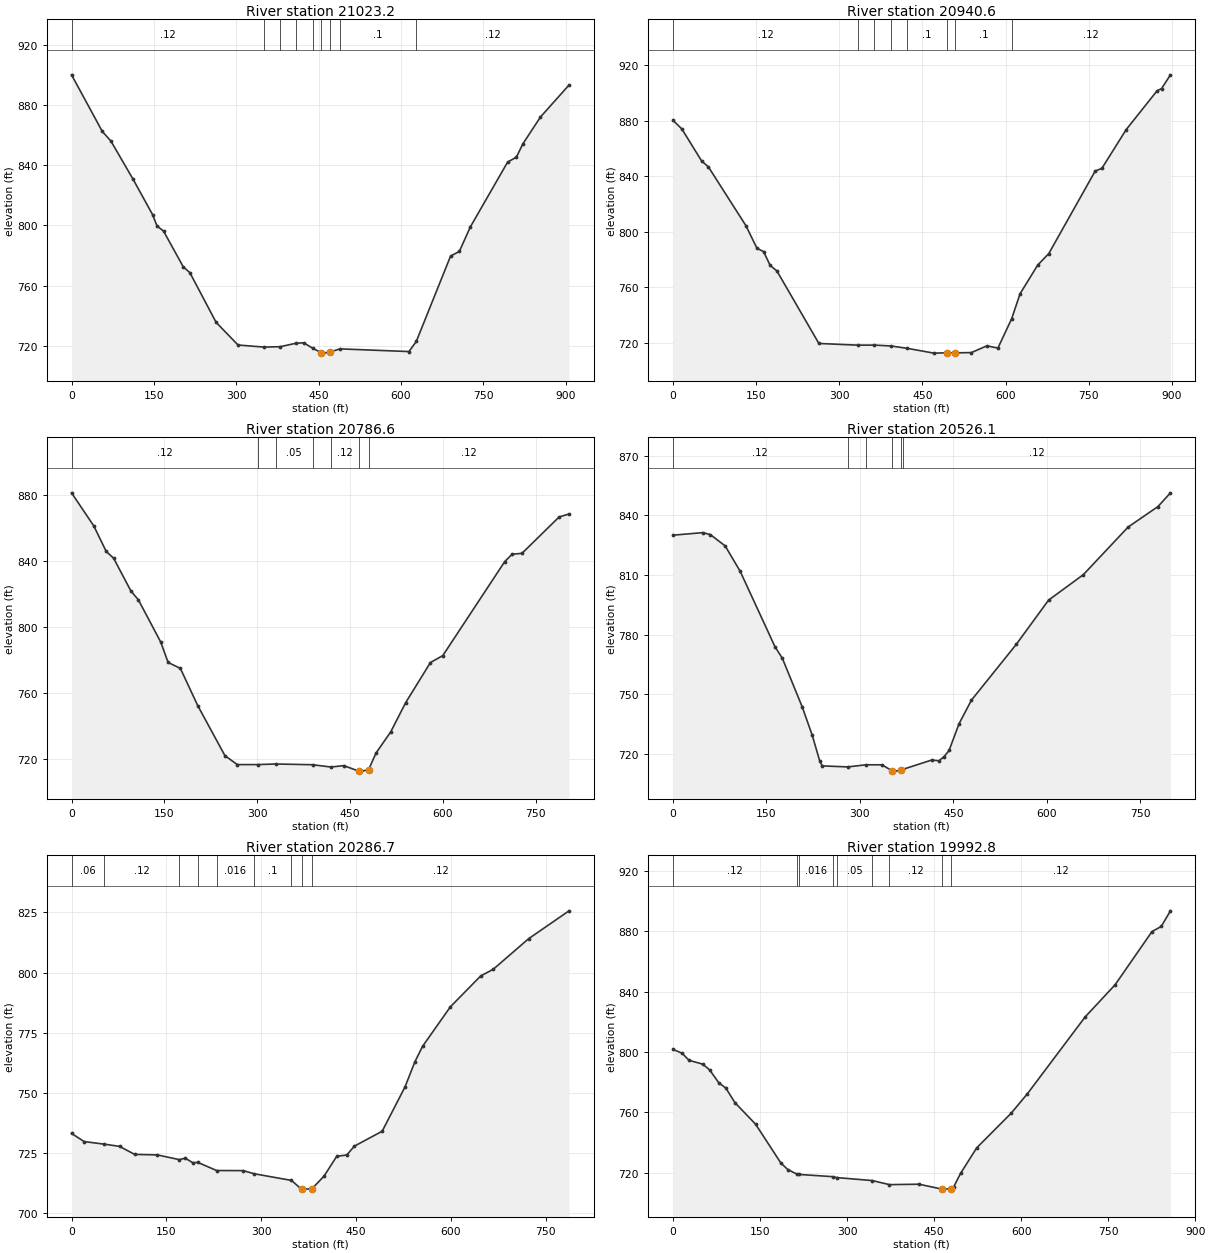
Type RM Length L Ch R = 1 ,21023.2 ,90.6,82.6,82.8
XS GIS Cut Line= 4
     1745089.365      433105.869     1745504.295      433094.584
     1745538.149      432996.494     1745922.698      432948.751
#Sta/Elev= 30
       0  900.23    55.9  862.64    71.8   856.1   111.8  830.94   147.7  807.17
   155.7  799.65   167.6  796.26   203.6  772.43   215.5  768.63   263.4  735.51
   303.3  720.42  350.64719.0398  380.19719.3025  409.73721.6608   423.1  721.88
  439.73718.1894     455  715.34     459  715.02     471  715.77  489.21717.8568
   614.7  716.06  628.16722.8208   690.6  779.61   706.6  782.72   726.6  799.02
   794.5  842.14   810.5  845.44   822.5  854.42   854.4  872.17   906.4  893.44
#Mann= 9 ,-1 , 0
       0     .12       0  350.64    .016       0  380.19     .12       0
  409.73      .1       0  439.73     .12       0     455    .045       0
     471     .12       0  489.21      .1       0  628.16     .12       0
Bank Sta=455,471
XS Rating Curve= 0 ,0
Exp/Cntr=0.3,0.1

Type RM Length L Ch R = 1 ,20940.6 ,115.7,154,183.6
XS GIS Cut Line= 4
     1745106.075      433164.463     1745564.408      433151.442
     1745598.262      433053.352     1745930.728      433011.685
#Sta/Elev= 30
       0  880.23      16  874.02    51.8  850.92    63.8   846.8   131.6  804.44
   151.5  788.18   163.5  785.78   175.4  775.78   187.4  771.92   263.2  719.68
  333.93718.4427  363.48718.5013  393.03 717.881  422.57716.1819   470.5  712.72
   493.6  712.94   508.6   712.9   538.3  713.12   566.3  717.96   586.2  716.38
  611.02737.5161   626.1  755.42     658   776.1     678  784.38   761.7  843.76
   773.7  845.66   817.6  873.58   873.4  901.53   881.4  903.06   897.4  912.96
#Mann= 8 ,-1 , 0
       0     .12       0  333.93    .016       0  363.48      .1       0
  393.03     .05       0  422.57      .1       0   493.6    .045       0
   508.6      .1       0  611.02     .12       0
Bank Sta=493.6,508.6
XS Rating Curve= 0 ,0
Exp/Cntr=0.3,0.1

Type RM Length L Ch R = 1 ,20786.6 ,258.8,260.5,261.7
XS GIS Cut Line= 2
     1745110.415      433231.303     1745912.498      433282.518
#Sta/Elev= 30
       0  881.48      36  861.36      56  845.89      68  841.77      96  821.81
     108   816.5     144  790.94     156   778.5   175.9  774.85   203.9  752.25
   247.9  721.84   267.9  716.47  300.53716.4716  330.13716.8369  389.32716.3819
  418.92714.9962   439.8  715.83   463.8  712.54   467.8   712.5   479.8  713.27
   491.8  723.41   515.8  736.45   539.8  754.09   579.8  778.44   599.8  782.67
   699.8  839.71   711.8  844.22   727.7  844.73   787.7  866.83   803.7  868.63
#Mann= 7 ,-1 , 0
       0     .12       0  300.53    .016       0  330.13     .05       0
  389.32      .1       0  418.92     .12       0   463.8    .045       0
   479.8     .12       0
Bank Sta=463.8,479.8
XS Rating Curve= 0 ,0
Exp/Cntr=0.3,0.1

Type RM Length L Ch R = 1 ,20526.1 ,240.4,239.5,238.3
XS GIS Cut Line= 2
     1745101.735      433456.129     1745896.005      433536.859
#Sta/Elev= 30
       0  830.04    47.9  831.32    59.9  830.35    83.8  824.64   107.8   811.9
   163.7  773.95   175.6  768.07   207.6  743.51   223.5   729.4   235.5  716.47
   239.5  713.95  280.51713.4467  310.19714.5191   335.3   714.5   351.3  711.56
   355.3  711.32   366.3  711.76  369.57712.2762   415.2   716.9   427.1  716.55
   435.1  718.62   443.1   721.7   459.1  735.15     479  747.02   550.9  775.08
   602.8  797.36   658.6  810.17   730.5  834.14   778.4  844.45   798.4  851.35
#Mann= 6 ,-1 , 0
       0     .12       0  280.51    .016       0  310.19      .1       0
   351.3    .045       0   366.3      .1       0  369.57     .12       0
Bank Sta=351.3,366.3
XS Rating Curve= 0 ,0
Exp/Cntr=0.3,0.1

Type RM Length L Ch R = 1 ,20286.7 ,293,293.8,295.2
XS GIS Cut Line= 2
     1745092.605      433700.711     1745878.196      433746.284
#Sta/Elev= 30
       0  733.22      20  729.84      52728.7573    75.9  727.85    99.9  724.51
   135.8  724.31  170.34722.3444   179.8  722.94   191.7  721.08  199.93721.1719
  229.51717.8212   271.6  717.78  288.68 716.496  347.85713.7137   363.5   710.1
   365.1  710.12   380.1  710.18   399.4  715.51   419.4   723.7   435.4  724.28
   447.4  727.95   491.3  734.12   527.3  752.44   543.2  763.02   555.2  769.37
   599.2  785.77   647.1  798.58   667.1  801.38     723  814.06   786.9  825.63
#Mann= 9 ,-1 , 0
       0     .06       0      52     .12       0  170.34     .06       0
  199.93     .12       0  229.51    .016       0  288.68      .1       0
  347.85     .12       0   365.1    .045       0   380.1     .12       0
Bank Sta=365.1,380.1
XS Rating Curve= 0 ,0
Exp/Cntr=0.3,0.1

Type RM Length L Ch R = 1 ,19992.8 ,315.6,334.3,348.7
XS GIS Cut Line= 3
     1745049.203      433846.111     1745300.939       433995.85
     1745863.005      434047.933
#Sta/Elev= 30
       0  801.68    15.8  799.15    27.7  794.45    51.5   791.9    63.3  788.05
    79.2  779.46      91  776.14   106.9  766.37   142.5  752.09     186  726.39
   197.9  722.07     214 718.968   217.6 718.824  275.38717.3648  282.73716.7294
  343.45714.7776  373.11712.0782   424.1  712.36   463.8   709.1   479.7  709.26
   483.7  710.48   495.6  719.49   523.5  736.46   583.1  759.49   610.9  772.31
   710.3  823.16     762  844.51   825.6  879.78   841.5  883.14   857.4  893.51
#Mann= 9 ,-1 , 0
       0     .12       0     214     .06       0   217.6    .016       0
  275.38     .12       0  282.73     .05       0  343.45      .1       0
  373.11     .12       0   463.8    .045       0   479.7     .12       0
Bank Sta=463.8,479.7
XS Rating Curve= 0 ,0
Exp/Cntr=0.3,0.1

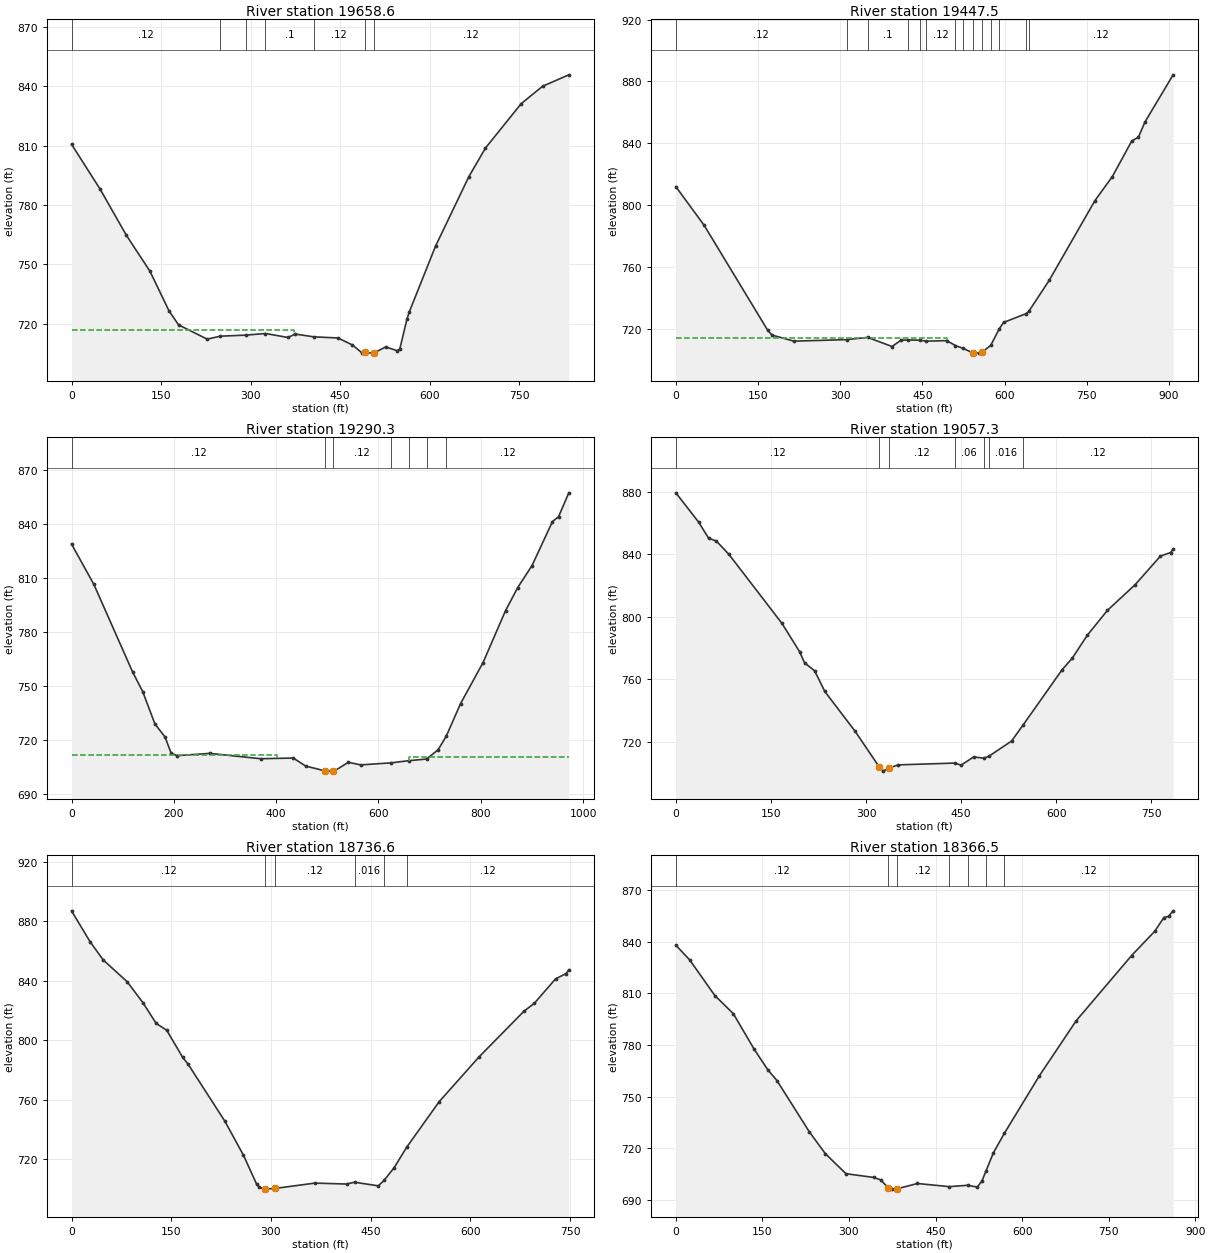
Type RM Length L Ch R = 1 ,19658.6 ,182.6,211.1,239.7
XS GIS Cut Line= 2
     1745004.491      433925.953     1745570.898       434536.63
#Sta/Elev= 30
       0   810.7    47.8  788.07    91.7   764.8   131.5  746.48   163.4  726.46
   179.3  719.45   227.2  712.26  249.34713.7436  292.78714.2947  324.82715.0923
   362.7  713.08   374.6  714.83  405.38713.4204   446.4  712.83   470.3  709.34
   486.2  705.39   491.4  705.51   506.1  705.18   506.4  705.21     526   708.3
     546  706.36     550  707.42   561.9   722.4   565.9  726.13   609.7  759.21
   665.5  794.32   693.4  808.81   753.2  831.22   789.1  840.01   832.9  845.78
#Mann= 7 ,-1 , 0
       0     .12       0  249.34    .016       0  292.78     .12       0
  324.82      .1       0  405.38     .12       0   491.4    .045       0
   506.4     .12       0
#XS Ineff= 2 , 0
          372.18  716.88
Permanent Ineff=
       F       F
Bank Sta=491.4,506.4
XS Rating Curve= 0 ,0
Exp/Cntr=0.3,0.1

Type RM Length L Ch R = 1 ,19447.5 ,153.6,157.2,160
XS GIS Cut Line= 4
     1744989.518      433940.927     1745242.122      434284.677
     1745143.163      434476.083      1745309.83      434683.114
#Sta/Elev= 30
       0  811.87    51.8  786.75   167.4     719   175.4  715.76   215.3  711.81
  311.63712.7926  350.26714.2295   394.7  708.34   410.6  712.35  423.56712.5892
  446.17712.4132  457.09711.8011   494.4  712.16  510.49  708.95  523.59707.2238
   542.3  704.23   553.7  704.05   558.3  704.56   574.8709.0335  590.09719.6157
   598.2  723.92  639.11729.5715  644.22731.0528   681.7  751.28     765  802.82
   796.8  818.39   832.5  841.58   844.4  843.87   856.3  853.72   907.8  884.32
#Mann= 14 ,-1 , 0
       0     .12       0  311.63    .016       0  350.26      .1       0
  423.56     .12       0  446.17      .1       0  457.09     .12       0
  510.49      .1       0  523.59     .12       0   542.3    .045       0
   558.3     .12       0   574.8      .1       0  590.09     .12       0
  639.11      .1       0  644.22     .12       0
#XS Ineff= 2 , 0
          495.59  714.06
Permanent Ineff=
       F       F
Bank Sta=542.3,558.3
XS Rating Curve= 0 ,0
Exp/Cntr=0.3,0.1

Type RM Length L Ch R = 1 ,19290.3 ,261.5,233.1,204
XS GIS Cut Line= 4
      1744928.32      433972.177      1745122.33      434239.104
      1744928.32      434550.302     1745105.403      434761.239
#Sta/Elev= 30
       0  829.08    43.7   806.6   119.3  758.07   139.2  747.08     163  729.18
   182.9  721.85   194.8  712.87   206.7  711.53   270.4   712.8   369.8  709.83
   433.6  710.21   457.5  705.78   496.5     703   511.5  703.01   513.4  702.94
   541.2  707.85   565.2   706.4  624.46707.5349  659.26  708.73  694.07709.6603
   716.7  714.83  732.35722.2056   760.6  740.48   804.5  763.22   848.4  792.02
   872.3   804.9   900.3  817.12   940.2  841.52   952.2  844.25   972.1  857.48
#Mann= 7 ,-1 , 0
       0     .12       0   496.5    .045       0   511.5     .12       0
  624.46     .06       0  659.26     .05       0  694.07    .016       0
  732.35     .12       0
#XS Ineff= 2 , 0
          402.25  711.76  659.43          710.69
Permanent Ineff=
       F       F
Bank Sta=496.5,511.5
XS Rating Curve= 0 ,0
Exp/Cntr=0.3,0.1

Type RM Length L Ch R = 1 ,19057.3 ,323.9,320.7,317.4
XS GIS Cut Line= 2
     1744639.257      434140.797      1745066.34      434798.349
#Sta/Elev= 30
       0  879.27    35.8  860.58    51.7   850.2    63.7  848.48    83.6  839.95
   167.2  795.81     195  777.72     203  770.51   218.9  765.39   234.8  752.24
   282.6  726.79   320.9  703.78   326.4  701.25   335.9  703.12   350.2  705.25
  439.59   706.4   449.8  705.09   469.6  710.33  485.63709.5286  493.81710.8194
   529.4  720.52  548.03731.0421     609  766.09   624.9   773.4   648.8  788.18
   680.6  804.12   724.4   820.6   764.2  838.83   780.1  841.08   784.1  843.37
#Mann= 7 ,-1 , 0
       0     .12       0   320.9    .045       0   335.9     .12       0
  439.59     .06       0  485.63      .1       0  493.81    .016       0
  548.03     .12       0
Bank Sta=320.9,335.9
XS Rating Curve= 0 ,0
Exp/Cntr=0.3,0.1

Type RM Length L Ch R = 1 ,18736.6 ,380.2,370.1,359.7
XS GIS Cut Line= 2
     1744362.137      434375.624     1744855.192      434938.124
#Sta/Elev= 30
       0  887.15    27.8   866.4    47.7  854.03    83.6  839.44   107.4  825.29
   127.3  811.31   143.2  806.71   167.1  788.51   175.1  784.02   230.8  745.34
   258.6  722.54   278.5  702.99   282.5  700.91   290.4  699.68   291.4  699.72
   306.4  700.16     366  703.74   413.8  703.11  425.68704.3475   461.5  701.89
  470.01 705.499   485.4  714.19  504.24727.9377     553  758.58   612.7   788.6
   680.4  819.45   696.3  824.92   728.1  841.32     744  844.88     748  847.35
#Mann= 6 ,-1 , 0
       0     .12       0   291.4    .045       0   306.4     .12       0
  425.68    .016       0  470.01      .1       0  504.24     .12       0
Bank Sta=291.4,306.4
XS Rating Curve= 0 ,0
Exp/Cntr=0.3,0.1

Type RM Length L Ch R = 1 ,18366.5 ,281.8,276.9,272.6
XS GIS Cut Line= 3
     1744181.575      434515.146     1744273.372      434832.854
      1744766.21      435030.771
#Sta/Elev= 30
       0  837.91    23.9  829.43    67.7  808.67    99.6  798.21   135.5   777.7
   159.4  765.62   175.3  759.36   231.1  729.76     259     717   294.8  705.36
   342.7  703.21   354.7  701.81   368.4  697.16   374.6  696.41   383.4  696.59
   418.6  699.68  473.77697.8555   505.6 698.644   522.4  697.59   530.4  701.12
  537.42706.8849   550.3   717.5  569.25728.7509   630.2   762.3   694.1  794.24
   789.9  831.96   829.8  845.96   845.8  853.98   853.8  854.62   861.8  857.88
#Mann= 7 ,-1 , 0
       0     .12       0   368.4    .045       0   383.4     .12       0
  473.77      .1       0   505.6    .016       0  537.42      .1       0
  569.25     .12       0
Bank Sta=368.4,383.4
XS Rating Curve= 0 ,0
Exp/Cntr=0.3,0.1

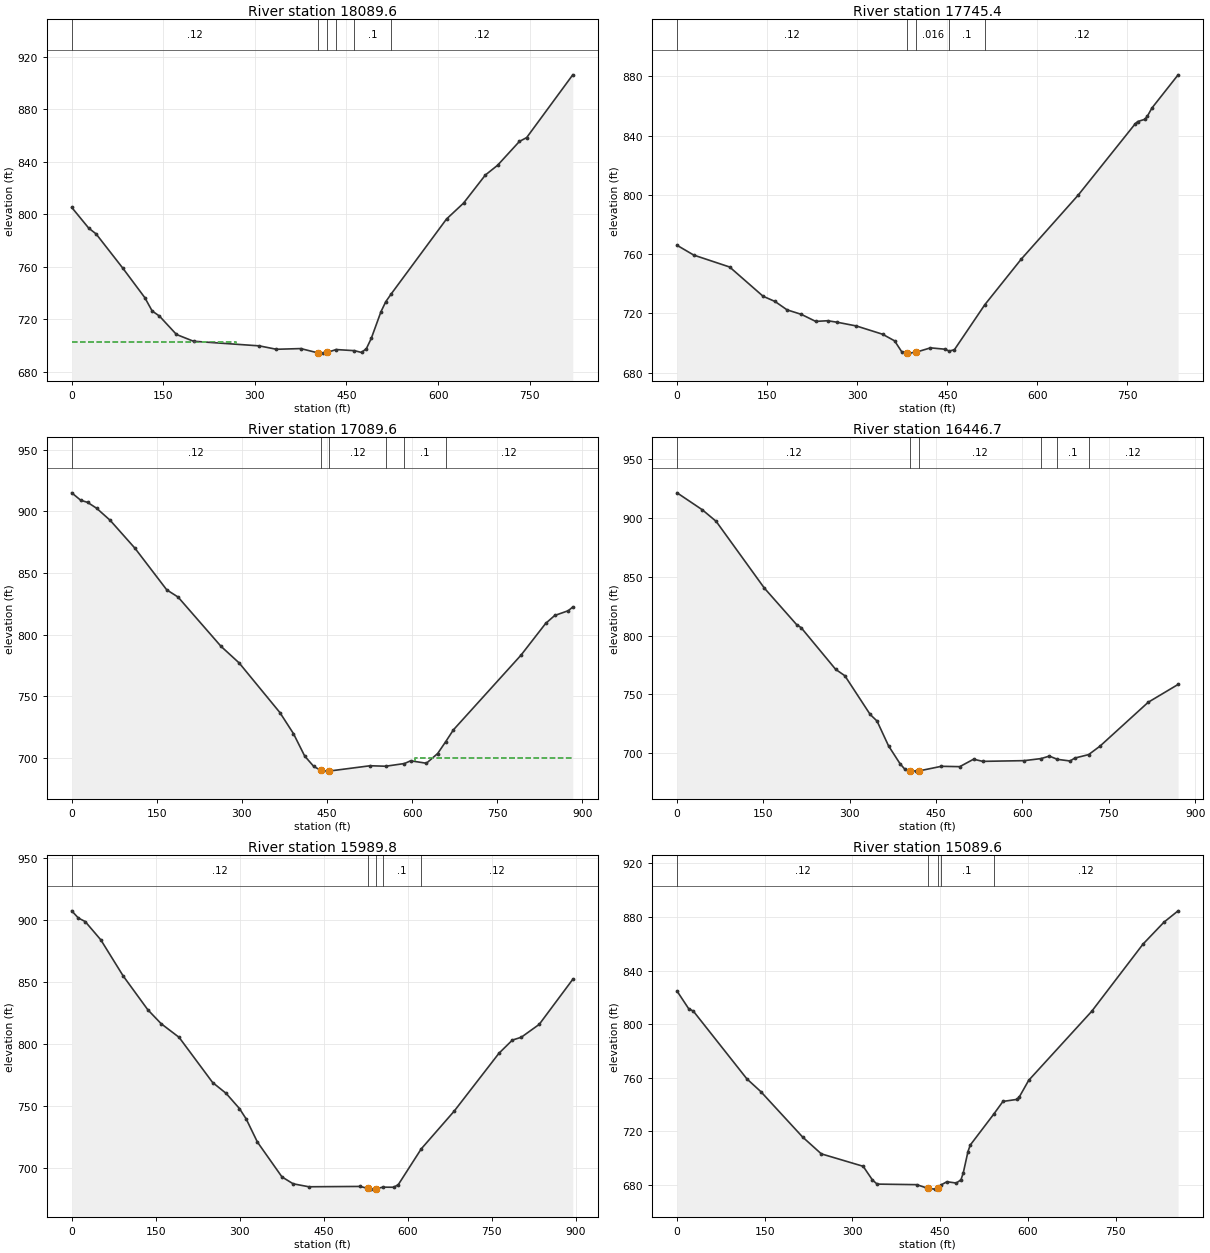
Type RM Length L Ch R = 1 ,18089.6 ,350.4,344.2,337.2
XS GIS Cut Line= 3
     1743921.273      435047.066     1744325.662       435120.54
     1744726.042      435207.124
#Sta/Elev= 30
       0  805.21    27.9   789.4    39.9  785.05    83.8  758.89   119.7  736.53
   131.7  726.41   143.6  722.52   171.6  708.48   199.5  703.34   307.3  699.82
   335.2  697.23   375.1  697.76   403.5  694.45     411   694.3   418.5  694.79
   432.9  697.03  463.12696.1696   474.6  694.81   482.6  697.73   490.6  705.52
   506.5  725.86   514.4  733.48  523.56739.5641   613.8  796.35   641.7  808.46
   677.5  829.87   697.4  837.24   733.2   855.4   745.1  858.34   820.6   906.1
#Mann= 6 ,-1 , 0
       0     .12       0   403.5    .045       0   418.5     .12       0
   432.9    .016       0  463.12      .1       0  523.56     .12       0
#XS Ineff= 2 , 0
          269.53  702.55
Permanent Ineff=
       F       F
Bank Sta=403.5,418.5
XS Rating Curve= 0 ,0
Exp/Cntr=0.3,0.1

Type RM Length L Ch R = 1 ,17745.4 ,654.9,655.8,647.3
XS GIS Cut Line= 3
     1743925.505      435499.756     1744448.508      435447.673
     1744739.307      435343.506
#Sta/Elev= 30
       0  765.96    27.9  759.34    87.6   751.3   143.3  731.54   163.2  728.01
   183.2  722.36     207  719.32   230.9  714.56   250.8  715.01   266.8  713.99
   298.6  711.48   342.4  705.88   362.3  701.42   374.3  693.97   383.1  693.28
   386.2  693.13   398.1  693.75   422.1   696.7     446  695.78  453.32694.5236
   461.9  695.43  512.68725.9023   573.1  756.56   668.2  799.92   763.2  848.12
   767.2  849.55     779  851.08     783  852.98   790.9  858.71   834.5  881.12
#Mann= 5 ,-1 , 0
       0     .12       0   383.1    .045       0   398.1    .016       0
  453.32      .1       0  512.68     .12       0
Bank Sta=383.1,398.1
XS Rating Curve= 0 ,0
Exp/Cntr=0.3,0.1

Type RM Length L Ch R = 1 ,17089.6 ,622.9,642.9,671
XS GIS Cut Line= 3
     1744042.879      436072.258     1744487.575      436030.879
     1744878.482      435836.563
#Sta/Elev= 30
       0  914.98      16  908.91    27.9  907.26    43.9  902.47    67.8  892.67
   111.6  869.98   167.5   836.3   187.4  830.48   263.2  790.46   295.1  777.03
   366.9   736.8   390.8  719.74   410.7  701.47   426.7  693.05   439.1   689.9
   450.6  689.27   454.1  689.34     526  693.63  553.56693.2428  586.55695.4335
   597.4  697.65   625.2  695.66     645  703.53  659.25713.1796   672.8  722.74
   791.9   783.3   835.5  809.12   851.4  815.51   875.2  819.36   883.2  822.39
#Mann= 6 ,-1 , 0
       0     .12       0   439.1    .045       0   454.1     .12       0
  553.56    .016       0  586.55      .1       0  659.25     .12       0
#XS Ineff= 2 , 0
                          604.31           699.8
Permanent Ineff=
       F       F
Bank Sta=439.1,454.1
XS Rating Curve= 0 ,0
Exp/Cntr=0.3,0.1

Type RM Length L Ch R = 1 ,16446.7 ,450.8,456.9,462.8
XS GIS Cut Line= 2
     1744013.757      436182.482     1744635.285      436791.857
#Sta/Elev= 30
       0  921.04    43.9  906.64    67.9  896.85   151.7  840.18   207.6   809.3
   215.6  806.63   275.5   771.3   291.5  765.87   335.4  733.08   347.4  727.43
   367.3  706.47   387.3  691.28   395.3   686.8   404.7  685.48   415.2  684.96
   419.7  685.09   459.2  689.05   491.1  688.76   515.1  695.07     531  693.24
   602.9  693.85  632.22695.5983   646.8  697.71  660.76694.9432   682.8  693.57
   690.8  696.02  714.95698.9813   734.7  706.15   818.5   743.4   870.4  758.51
#Mann= 6 ,-1 , 0
       0     .12       0   404.7    .045       0   419.7     .12       0
  632.22     .06       0  660.76      .1       0  714.95     .12       0
Bank Sta=404.7,419.7
XS Rating Curve= 0 ,0
Exp/Cntr=0.3,0.1

Type RM Length L Ch R = 1 ,15989.8 ,907.5,900.2,888.3
XS GIS Cut Line= 2
     1743792.035      436374.955     1744250.368      437143.184
#Sta/Elev= 30
       0   907.7      12  901.81      24  899.07    51.9  884.27    91.8  855.13
   135.8  827.77   159.7  816.46   191.7  805.46   251.6  768.93   275.6  760.21
   299.5  747.88   311.5   739.5   331.5  720.85   375.4  692.64   395.4  687.07
   423.3  684.68   515.2  684.95     529  683.29   535.1  682.77     544  683.11
  555.29684.3585   575.1  684.29   583.1  686.41  624.08715.3248   682.9  745.82
   762.8  792.58   786.7  803.21   802.7  805.53   834.7  815.92   894.6  852.34
#Mann= 5 ,-1 , 0
       0     .12       0     529    .045       0     544     .12       0
  555.29      .1       0  624.08     .12       0
Bank Sta=529,544
XS Rating Curve= 0 ,0
Exp/Cntr=0.3,0.1

Type RM Length L Ch R = 1 ,15089.6 ,384.3,367,336.1
XS GIS Cut Line= 3
     1743057.173      436925.745     1743387.288      437206.956
      1743742.91      437436.554
#Sta/Elev= 30
       0  824.74    19.9   811.6    27.8  809.84   119.4  759.27   143.2  749.78
   214.8  715.85   246.7  703.32   318.3  694.04   334.2  683.82   342.2  680.75
   409.8  680.33   429.7  677.52   441.2     677   445.6  677.71  451.07680.0157
   461.6  682.52   477.6  681.53   485.6  683.98   489.6  689.27   497.6  705.06
   501.5  709.89  541.25732.7119   557.4  742.43   581.4  743.95   585.4   745.8
   601.4  758.16   709.2  809.66     797  859.83     833  876.26     857  884.64
#Mann= 5 ,-1 , 0
       0     .12       0   429.7    .045       0   445.6     .12       0
  451.07      .1       0  541.25     .12       0
Bank Sta=429.7,445.6
XS Rating Curve= 0 ,0
Exp/Cntr=0.3,0.1

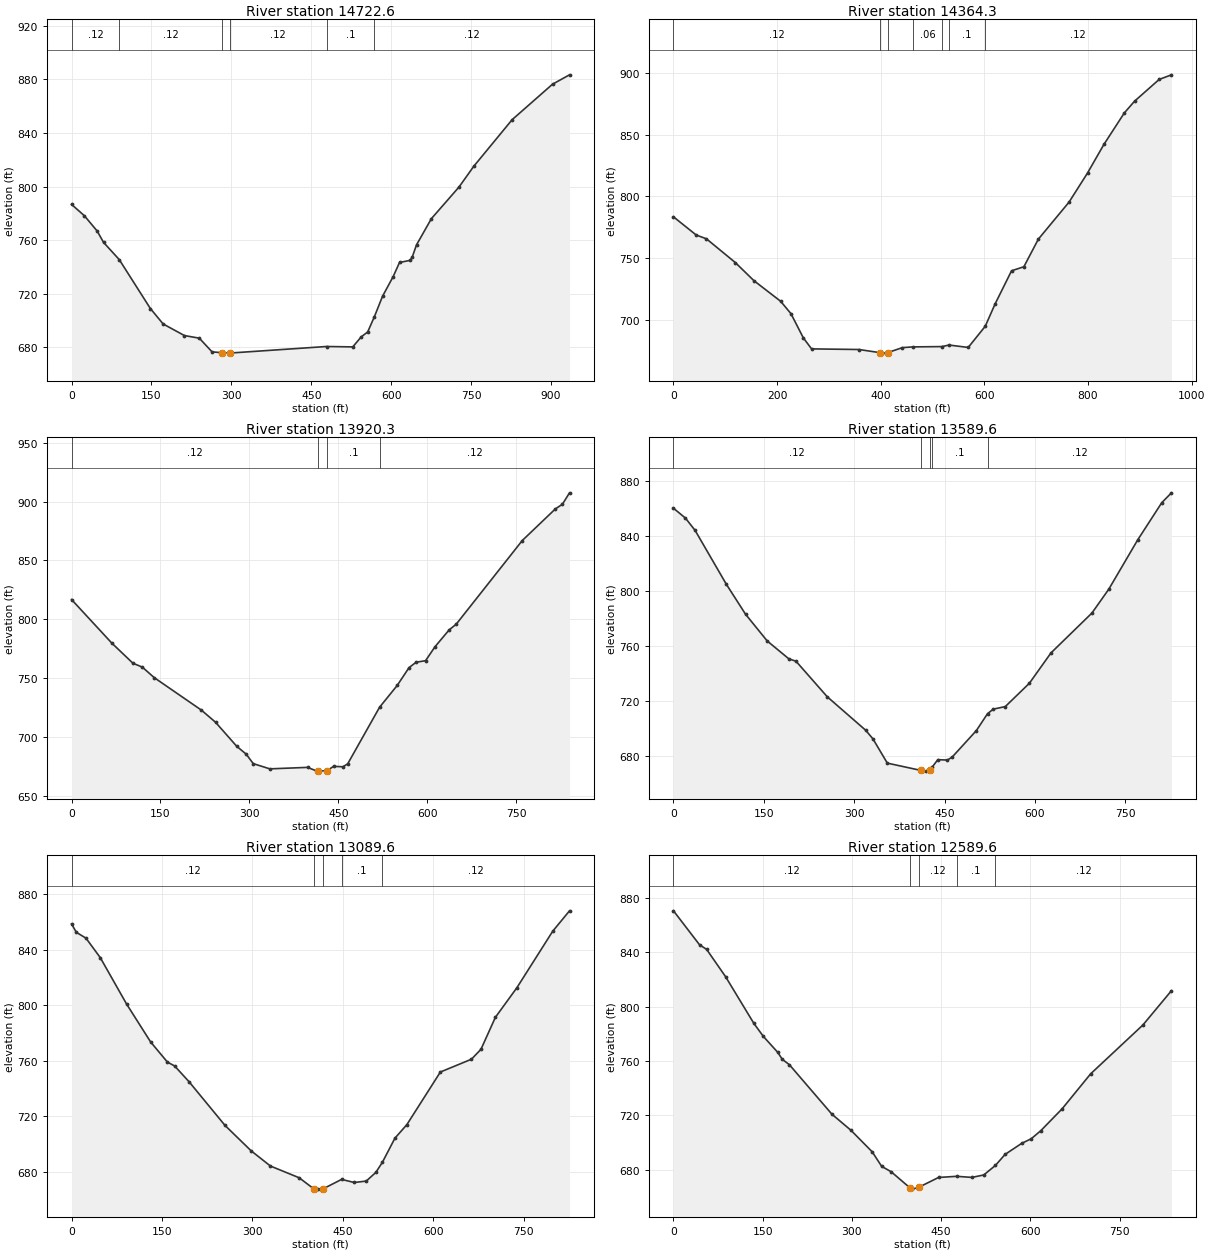
Type RM Length L Ch R = 1 ,14722.6 ,371,358.3,361.7
XS GIS Cut Line= 4
     1742837.176      437216.293     1742990.821      437362.126
     1743350.196      437419.418     1743708.269      437444.157
#Sta/Elev= 30
       0  786.65      24  778.24      48  766.85      60  758.36   89.57745.4741
   147.9  709.03   171.9   697.5   211.8  688.86   239.8   686.9   263.8  676.66
   282.5  676.11   295.8  675.75   297.5  675.81  478.59680.6886   527.8  680.39
   543.8  687.91   555.8  691.51  568.31702.7991   583.7  718.14   603.7  732.87
   615.6  743.36   635.6  744.95   639.6  747.55   647.5  756.49   675.4  776.04
   727.3  799.65   755.2  815.22     827  849.86   902.8  876.32   934.7  883.31
#Mann= 6 ,-1 , 0
       0     .12       0   89.57     .12       0   282.5    .045       0
   297.5     .12       0  478.59      .1       0  568.31     .12       0
Bank Sta=282.5,297.5
XS Rating Curve= 0 ,0
Exp/Cntr=0.3,0.1

Type RM Length L Ch R = 1 ,14364.3 ,443.2,444,444
XS GIS Cut Line= 3
     1742863.217      437866.032      1743465.84      437486.742
      1743714.78      437491.032
#Sta/Elev= 30
       0   783.5    43.8  768.77    63.6  765.69   119.3  746.45   155.1   731.8
   206.8  715.05   226.7     705   250.6  685.35   266.5  676.46     358  675.95
   398.7  673.39   409.7  673.02   413.7  673.48   441.6  677.47  462.03678.0748
  517.81678.3166  531.83 679.568   568.8  677.63  601.63694.7986   620.6  712.85
   652.4  739.77   676.2  743.05   704.1  765.41   763.4  795.47     799  819.02
   830.6  842.19   870.1  867.78   889.9  877.31   937.3  894.91     961  898.64
#Mann= 7 ,-1 , 0
       0     .12       0   398.7    .045       0   413.7     .12       0
  462.03     .06       0  517.81     .12       0  531.83      .1       0
  601.63     .12       0
Bank Sta=398.7,413.7
XS Rating Curve= 0 ,0
Exp/Cntr=0.3,0.1

Type RM Length L Ch R = 1 ,13920.3 ,330.8,330.7,336.3
XS GIS Cut Line= 2
     1743100.196      438198.063     1743826.759      437776.188
#Sta/Elev= 30
       0  816.65    67.7  779.71   103.5   762.5   119.4  759.18   139.4  750.26
     219  722.63   242.9  712.32   278.7  691.84   294.6  685.19   306.6   677.1
   334.5  672.66   398.2  673.92   414.1  670.73     416  670.81     431  671.06
     442  674.77   457.9  674.44   465.9  676.91  519.66725.0287   549.5  743.63
   569.4  758.73   581.3  763.33   597.3  764.65   613.2  776.49   637.1  790.84
     649  795.68   760.5  866.85   816.3  893.72   828.2   897.7   840.2  907.41
#Mann= 4 ,-1 , 0
       0     .12       0     416    .045       0     431      .1       0
  519.66     .12       0
Bank Sta=416,431
XS Rating Curve= 0 ,0
Exp/Cntr=0.3,0.1

Type RM Length L Ch R = 1 ,13589.6 ,501.2,500,494.4
XS GIS Cut Line= 3
     1743202.657      438487.058     1743568.956      438284.019
     1743961.932      438174.852
#Sta/Elev= 30
       0  860.28    19.9  853.07    35.9  844.15    87.8  804.99   119.7  783.22
   155.6  763.84   191.5  750.87   203.4  749.12   255.3  723.29   319.1  698.97
   331.1  692.73     355   675.1   411.3  669.76   418.8  669.29   426.3   670.3
  429.37 672.149   438.8  677.62   454.8  677.32   462.8  679.57   502.8  698.74
  521.33711.0054   530.8  714.31   550.8  716.17   590.8  733.11   626.7  755.18
   694.7  784.14   722.7  801.48   770.7   837.3   810.7  864.34   826.7  871.46
#Mann= 5 ,-1 , 0
       0     .12       0   411.3    .045       0   426.3     .12       0
  429.37      .1       0  521.33     .12       0
Bank Sta=411.3,426.3
XS Rating Curve= 0 ,0
Exp/Cntr=0.3,0.1

Type RM Length L Ch R = 1 ,13089.6 ,505.7,500,500.9
XS GIS Cut Line= 3
     1743407.329      438956.102     1743752.222      438735.272
      1744116.47       438533.05
#Sta/Elev= 30
       0  858.56       8  852.54    23.9  848.37    47.7  834.27    91.4  800.78
   131.2  773.52     159  759.03     171  756.21   194.8  744.92   254.5   713.4
   298.2  694.94     330  684.06   377.7   675.6     402   667.6   409.5  667.42
     417  667.56  448.03674.4315     469   672.2   488.9  673.22   504.8  679.45
  515.59686.6652   536.5  704.14   556.3  713.89   611.9  751.84   663.5  761.08
   679.3  768.25   703.2  791.28   738.9  812.63   798.4  853.41   826.2  868.06
#Mann= 5 ,-1 , 0
       0     .12       0     402    .045       0     417     .12       0
  448.03      .1       0  515.59     .12       0
Bank Sta=402,417
XS Rating Curve= 0 ,0
Exp/Cntr=0.3,0.1

Type RM Length L Ch R = 1 ,12589.6 ,446.8,451.2,447.6
XS GIS Cut Line= 3
     1743621.633      439471.855     1743899.269      439176.041
     1744290.557      438994.229
#Sta/Elev= 30
       0  870.36    43.8   845.4    55.7  842.03    87.5  822.02   135.2   787.6
   151.1  778.08     175  766.52     183  761.21   194.9  757.28   266.5  720.87
   298.3  709.14   334.1  693.29     350  682.61   365.9  678.68   398.2   666.6
   401.7  665.89   413.2  667.43   445.6  674.46  476.07675.2968   501.6  674.51
   521.6  676.29   541.2683.2902   557.5  691.41   585.5  699.54   601.4  702.88
   617.4  708.77   653.4   724.9   701.3  750.58   789.2  786.48   837.2  811.69
#Mann= 5 ,-1 , 0
       0     .12       0   398.2    .045       0   413.2     .12       0
  476.07      .1       0   541.2     .12       0
Bank Sta=398.2,413.2
XS Rating Curve= 0 ,0
Exp/Cntr=0.3,0.1