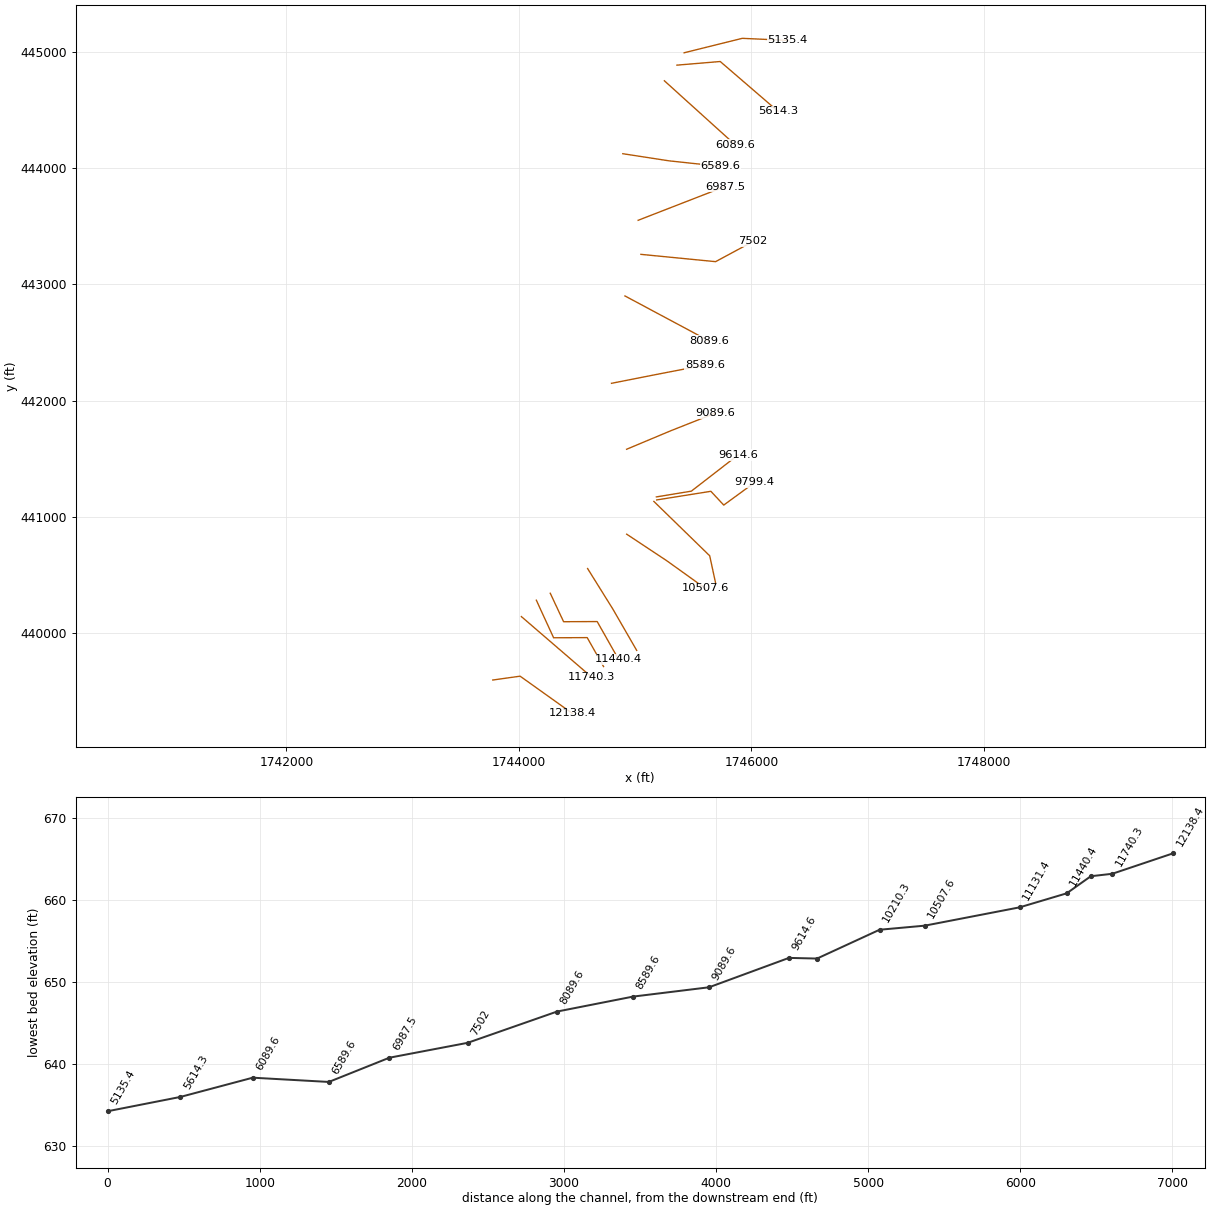
HEC-RAS study FORKCK.prj: FORKCK

--- FORKCK.g01 (geometry) --- (continued)

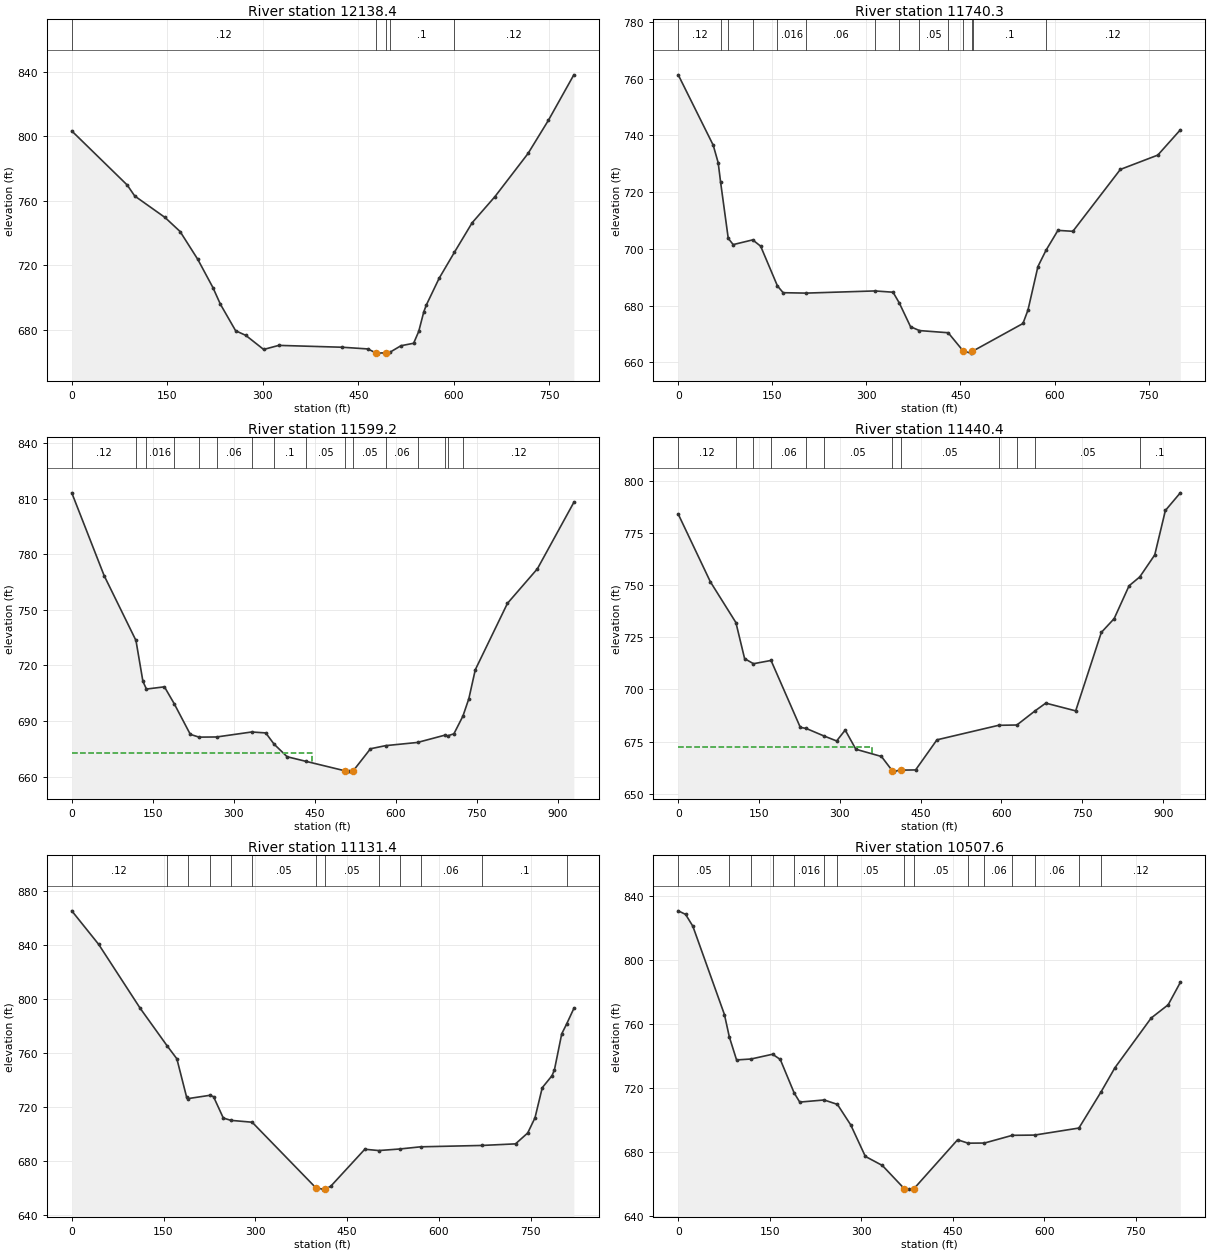
Type RM Length L Ch R = 1 ,12138.4 ,400,398.1,394.9
XS GIS Cut Line= 3
      1743775.11      439599.322     1744010.176      439632.319
     1744458.939      439312.575
#Sta/Elev= 30
       0  803.32      87  769.85    98.9  763.02   146.4  749.74   170.1  741.03
   197.8  723.84   221.6  706.35   233.4     696   257.3  679.58   273.3   676.7
   301.3  667.99   325.2  670.51     425  669.35     465   668.3     477  665.94
   480.9  665.71   492.9  665.96  499.04 666.126   516.9  670.29   536.8  671.82
   544.8  679.14   552.8  691.32   556.8  695.55   576.8  712.02  600.84728.1606
   628.7  746.45   664.6   762.7   716.5  789.38   748.5  809.95   788.4  838.08
#Mann= 5 ,-1 , 0
       0     .12       0     477    .045       0   492.9     .12       0
  499.04      .1       0  600.84     .12       0
Bank Sta=477,492.9
XS Rating Curve= 0 ,0
Exp/Cntr=0.3,0.1

Type RM Length L Ch R = 1 ,11740.3 ,123.6,141.1,158.4
XS GIS Cut Line= 2
     1744020.788      440144.823     1744627.559      439622.688
#Sta/Elev= 30
       0  761.36    55.8  736.53    63.7  730.36   67.61  723.41   79.73703.7024
    87.6  701.49   118.7 703.156   131.4  700.93  158.18 686.914   167.3  684.53
  203.46684.3845  313.53685.1521   342.5   684.7  352.49680.8881   370.4  672.53
  384.58671.1758  430.42670.4068   454.1  664.04     466  663.22   469.1  663.84
  469.39 663.898   549.6  673.67   557.6   678.4   573.5  693.76  586.28699.4547
   605.4  706.51   629.2  706.18   704.9     728   764.6  733.05   800.5  741.95
#Mann= 14 ,-1 , 0
       0     .12       0   67.61      .1       0   79.73    .016       0
   118.7     .06       0  158.18    .016       0  203.46     .06       0
  313.53     .05       0  352.49     .12       0  384.58     .05       0
  430.42     .12       0   454.1    .045       0   469.1     .12       0
  469.39      .1       0  586.28     .12       0
Bank Sta=454.1,469.1
XS Rating Curve= 0 ,0
Exp/Cntr=0.3,0.1

Type RM Length L Ch R = 1 ,11599.2 ,158.3,158.8,164.3
XS GIS Cut Line= 4
     1744149.695      440285.448     1744298.132      439962.531
     1744587.195      439963.833      1744727.82      439715.135
#Sta/Elev= 30
       0  813.21    59.9  768.55  118.93  733.47   131.8  711.42   138.3707.2412
   171.7  708.44  189.65699.4041   219.6  682.78  235.82681.2772  268.32681.3629
  333.33684.0582   359.4  683.55  374.78677.5079     399  670.69  433.85668.2062
   505.9  663.11   513.8  662.92   521.7  663.19   553.4     675  581.53676.6846
   640.6678.4083  690.79 682.309  696.62681.9971     708  683.08  724.72692.6547
   735.7  702.09   747.6  717.66   807.2  753.53   862.7   772.2   930.2  808.07
#Mann= 16 ,-1 , 0
       0     .12       0  118.93      .1       0   138.3    .016       0
  189.65     .06       0  235.82    .016       0  268.32     .06       0
  333.33     .05       0  374.78      .1       0  433.85     .05       0
   505.9    .045       0   521.7     .05       0  581.53     .06       0
   640.6     .05       0  690.79      .1       0  696.62     .05       0
  724.72     .12       0
#XS Ineff= 2 , 0
          444.85  672.56
Permanent Ineff=
       F       F
Bank Sta=505.9,521.7
XS Rating Curve= 0 ,0
Exp/Cntr=0.3,0.1

Type RM Length L Ch R = 1 ,11440.4 ,333.8,308.9,278.6
XS GIS Cut Line= 4
     1744269.486      440345.344      1744384.07      440100.552
     1744673.132      440101.854     1744856.726      439777.635
#Sta/Elev= 30
       0  784.07    59.6  751.63  107.04732.0601   123.2  714.77  139.65712.3323
  172.26713.8976   226.6   681.8  237.48681.3035   270.1677.7275     294   675.3
   309.9  680.53   329.7  671.32   377.2  667.85     397  661.12     401  660.83
   412.8   661.3   440.6  661.41   480.2  675.84  594.59682.7994  628.53682.9441
  662.47689.7606   682.2  693.44   737.7  689.72   785.3  727.34   809.1  733.95
   836.8   749.7  856.63 753.946   884.4  764.48   904.2  785.81   931.9  794.27
#Mann= 12 ,-1 , 0
       0     .12       0  107.04      .1       0  139.65    .016       0
  172.26     .06       0  237.48    .016       0   270.1     .05       0
     397    .045       0   412.8     .05       0  594.59    .016       0
  628.53     .06       0  662.47     .05       0  856.63      .1       0
#XS Ineff= 2 , 0
          360.13  672.31
Permanent Ineff=
       F       F
Bank Sta=397,412.8
XS Rating Curve= 0 ,0
Exp/Cntr=0.3,0.1

Type RM Length L Ch R = 1 ,11131.4 ,614.2,623.8,634.1
XS GIS Cut Line= 3
     1744590.665      440557.554     1744808.301      440208.609
     1745012.783      439854.174
#Sta/Elev= 30
       0   865.4    43.9  840.58   111.8  793.17   155.5 765.528   171.7  755.75
   187.7  727.23  190.31726.2396  225.12728.6234   231.6  727.68   247.6  711.83
  259.93710.1015  294.74708.7088   399.2  659.94   411.2  659.12   414.2  659.22
   423.2  661.26   478.8  688.67   501.7687.7183   535.8688.8645   569.9690.4788
   670.3691.4938   725.1  692.67     745  700.74   756.9  711.96   768.8  734.32
   784.7  743.18   788.7   747.6   800.6  774.24  808.59781.4982   820.4  793.06
#Mann= 13 ,-1 , 0
       0     .12       0   155.5      .1       0  190.31    .016       0
  225.12     .06       0  259.93    .016       0  294.74     .05       0
   399.2    .045       0   414.2     .05       0   501.7     .06       0
   535.8    .016       0   569.9     .06       0   670.3      .1       0
  808.59     .12       0
Bank Sta=399.2,414.2
XS Rating Curve= 0 ,0
Exp/Cntr=0.3,0.1

Type RM Length L Ch R = 1 ,10507.6 ,301.5,297.3,293.1
XS GIS Cut Line= 3
     1744926.992      440852.982     1745272.305      440624.338
     1745604.431       440386.34
#Sta/Elev= 30
       0  830.53      12  828.32    23.9  820.97    75.7  765.82   83.75751.8204
    95.6   737.5  119.17738.0645   154.6741.0488   167.2   737.8  190.02 716.876
   199.1  711.19  239.12712.5099  260.86709.7476   282.7  696.94   306.6  677.31
   334.5  671.64   370.4  657.19   378.3  656.88   386.3  657.16   457.8  687.67
  474.93685.5601  501.78685.6329   547.6690.4548  583.94690.6017  656.61 694.988
  692.95717.5749   715.6   732.6   775.1  763.67   802.9   771.9   822.8  785.86
#Mann= 15 ,-1 , 0
       0     .05       0   83.75     .06       0  119.17    .016       0
   154.6     .06       0  190.02    .016       0  239.12     .06       0
  260.86     .05       0   370.4    .045       0   386.3     .05       0
  474.93      .1       0  501.78     .06       0   547.6    .016       0
  583.94     .06       0  656.61     .05       0  692.95     .12       0
Bank Sta=370.4,386.3
XS Rating Curve= 0 ,0
Exp/Cntr=0.3,0.1

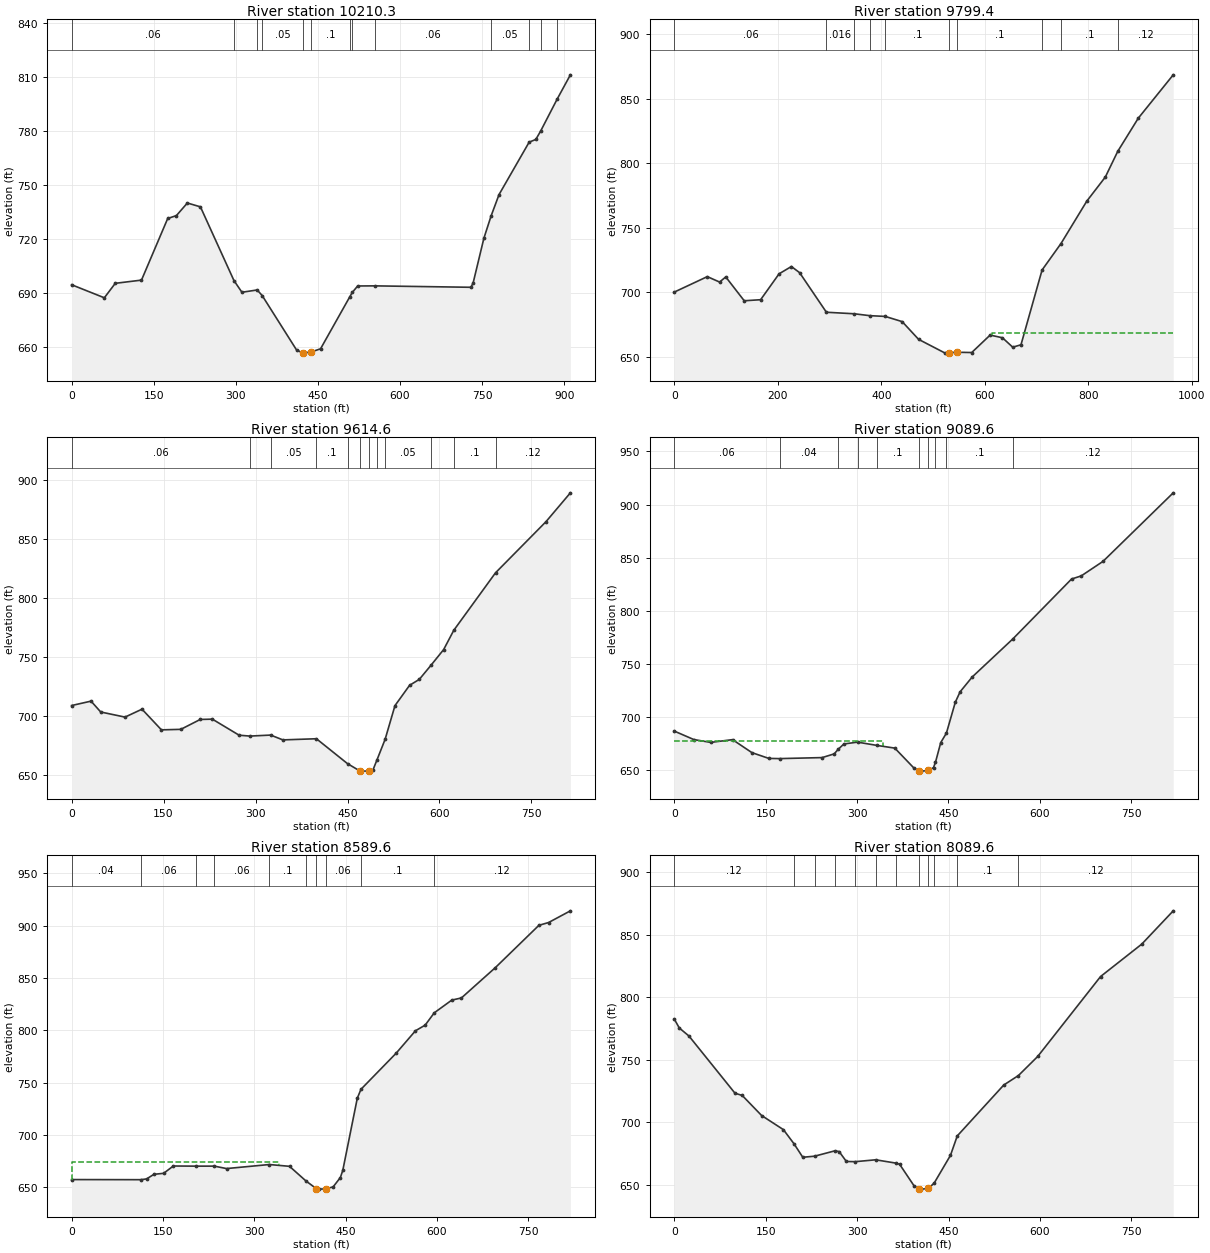
Type RM Length L Ch R = 1 ,10210.3 ,416.3,410.9,405.6
XS GIS Cut Line= 3
     1745160.762      441134.623     1745641.231      440667.175
     1745692.012      440431.498
#Sta/Elev= 30
       0  694.43    59.8  687.17    79.8  695.22   127.7     697   175.6  731.28
   191.5   732.9   211.5   739.9   235.4  737.76  296.71696.7106   311.2  690.25
  339.07691.5129  348.17 688.437     411  658.16   422.6  656.38   437.6  657.02
   454.9  658.79  508.49687.8173     513690.1857   522.7  693.74  554.21693.8012
   729.6  693.01   733.6  695.32   753.3  720.26  766.38732.5883     781  744.58
  836.06 773.762   848.2  775.25  857.02779.9102  887.23797.7161   911.4  811.21
#Mann= 13 ,-1 , 0
       0     .06       0  296.71    .016       0  339.07     .06       0
  348.17     .05       0   422.6    .045       0   437.6      .1       0
  508.49     .05       0     513    .016       0  554.21     .06       0
  766.38     .05       0  836.06     .12       0  857.02     .05       0
  887.23     .12       0
Bank Sta=422.6,437.6
XS Rating Curve= 0 ,0
Exp/Cntr=0.3,0.1

Type RM Length L Ch R = 1 ,9799.4  ,146.6,184.8,223.1
XS GIS Cut Line= 4
     1745185.104      441147.347      1745651.25      441221.565
     1745761.927      441103.076     1746028.582       441297.89
#Sta/Elev= 30
       0  700.23    63.5  712.15    87.3  707.95    99.2  711.91   134.9  693.44
   166.6  694.26   202.3  714.34   226.1  719.99     242  715.21  293.77684.5465
  347.68683.3608  377.59681.8994  407.49  681.31   440.3  677.28     472  663.55
   523.4  652.86   531.6  653.24   546.6  653.52   574.8  653.33   610.4  666.86
   634.2  664.76     654  657.47     670  659.32   710.8717.2951  747.38737.8133
   797.3  770.69   833.1  789.34  857.11809.2633   896.8  834.95   964.4  868.56
#Mann= 10 ,-1 , 0
       0     .06       0  293.77    .016       0  347.68     .06       0
  377.59     .05       0  407.49      .1       0   531.6    .045       0
   546.6      .1       0   710.8     .05       0  747.38      .1       0
  857.11     .12       0
#XS Ineff= 2 , 0
                          614.02           668.7
Permanent Ineff=
       F       F
Bank Sta=531.6,546.6
XS Rating Curve= 0 ,0
Exp/Cntr=0.3,0.1

Type RM Length L Ch R = 1 ,9614.6  ,530.9,525,518.6
XS GIS Cut Line= 3
       1745182.5      441173.388     1745483.281      441222.867
     1745885.625      441534.065
#Sta/Elev= 30
       0  708.62    31.7  712.35    47.5  703.13    87.1   698.8   114.8  705.52
   146.5  687.97   178.1   688.4   209.8   696.8   229.6  697.06   273.2  683.43
  290.74682.6879   324.6  683.54   344.6  679.45  399.28680.4263  449.99659.2897
   470.3  653.04   471.7  652.94   485.3  653.01   491.6  654.04  498.26662.7535
  511.29679.8926   527.4  708.55   551.2  725.76   567.1  730.83  585.97742.6909
   606.8  756.12  623.31 772.478  691.37821.2665   773.7  864.68   813.5  889.16
#Mann= 12 ,-1 , 0
       0     .06       0  290.74    .016       0   324.6     .05       0
  399.28      .1       0  449.99     .05       0   470.3    .045       0
   485.3     .05       0  498.26      .1       0  511.29     .05       0
  585.97     .06       0  623.31      .1       0  691.37     .12       0
Bank Sta=470.3,485.3
XS Rating Curve= 0 ,0
Exp/Cntr=0.3,0.1

Type RM Length L Ch R = 1 ,9089.6  ,504.5,500,495.8
XS GIS Cut Line= 3
     1744926.202      441582.939     1745303.925      441741.056
      1745684.84       441891.64
#Sta/Elev= 30
       0  686.93    31.8  679.04    59.6  676.36    95.4  678.96   127.2  666.74
     155   661.3  172.61661.1254   242.5  662.08   262.4  665.58  268.66669.7759
   278.3   674.9  300.68676.6127   332.7673.5145   361.8     671   393.6  652.03
     402  649.67   405.5  649.35     417  649.95   425.4  652.71   428.6 657.566
   437.3  676.19  446.62685.1077   461.2  714.14   469.1  723.94     489   737.9
  555.64773.6452   652.1  829.99     668  832.92   703.8   846.6   819.1  911.04
#Mann= 10 ,-1 , 0
       0     .06       0  172.61     .04       0  268.66    .016       0
  300.68     .06       0   332.7      .1       0     402    .045       0
     417      .1       0   428.6     .06       0  446.62      .1       0
  555.64     .12       0
#XS Ineff= 2 , 0
           342.8  677.93
Permanent Ineff=
       F       F
Bank Sta=402,417
XS Rating Curve= 0 ,0
Exp/Cntr=0.3,0.1

Type RM Length L Ch R = 1 ,8589.6  ,515.6,500,484.5
XS GIS Cut Line= 3
     1744796.389      442149.862     1745198.177      442228.955
     1745600.246      442306.629
#Sta/Elev= 30
       0  657.34  113.96657.2336   123.2  657.98   135.2  662.37   151.1  663.31
     167  670.31  204.27670.1764  234.37670.1909   254.4  667.86  324.68671.7206
   357.8     670  384.88655.9735     402   648.6   405.5  648.21     417  648.44
   429.4  650.36   441.3  659.28   445.3   666.2   469.1  735.09  475.15743.6332
   532.8  778.05   564.6  799.54   580.5  804.92  595.47816.6983   624.2  828.84
   640.1  830.93   695.8   859.9   767.3  900.33   783.2     903     819  914.17
#Mann= 10 ,-1 , 0
       0     .04       0  113.96     .06       0  204.27    .016       0
  234.37     .06       0  324.68      .1       0  384.88     .06       0
     402    .045       0     417     .06       0  475.15      .1       0
  595.47     .12       0
#XS Ineff= 2 , 0
          339.86  674.51
Permanent Ineff=
       F       F
Bank Sta=402,417
XS Rating Curve= 0 ,0
Exp/Cntr=0.3,0.1

Type RM Length L Ch R = 1 ,8089.6  ,578.9,587.5,595.7
XS GIS Cut Line= 3
     1744912.153      442900.869     1745273.304       442707.84
     1745634.455      442514.811
#Sta/Elev= 30
       0  782.33       8  775.42    23.8  769.02    99.4   723.2   111.3   721.4
   143.1  705.35   178.9  694.02  196.46682.5947   210.7   671.9  229.95672.7505
  263.44677.0544   270.4  676.46   282.3  668.52  296.93668.3733  330.42669.8711
  363.91667.1917   369.7  666.29   393.6  648.88     402  646.44   405.5  646.38
     417  646.95  426.46651.2357   453.2  673.43  464.38688.9999   540.7  729.75
  564.85737.3843   596.4  752.61   699.7  816.67   767.3  842.61     819  869.28
#Mann= 12 ,-1 , 0
       0     .12       0  196.46     .05       0  229.95     .06       0
  263.44     .05       0  296.93    .016       0  330.42     .05       0
  363.91      .1       0     402    .045       0     417      .1       0
  426.46     .06       0  464.38      .1       0  564.85     .12       0
Bank Sta=402,417
XS Rating Curve= 0 ,0
Exp/Cntr=0.3,0.1

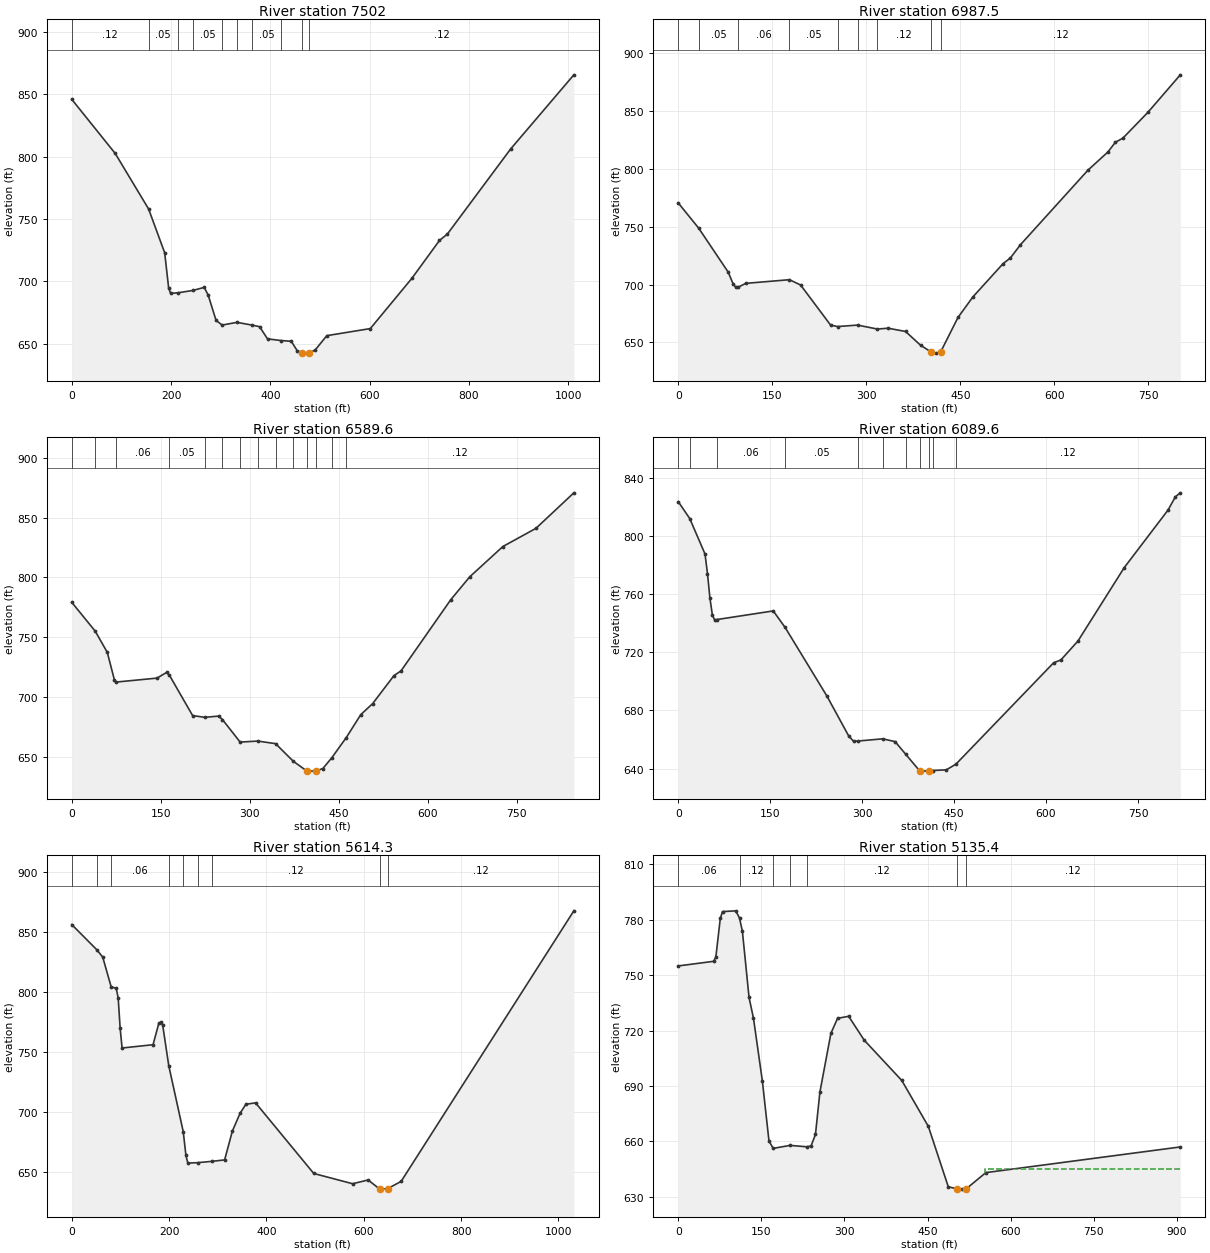
Type RM Length L Ch R = 1 ,7502    ,502.9,514.6,526.2
XS GIS Cut Line= 3
     1745049.527      443258.418     1745691.788      443195.671
     1746014.371      443369.096
#Sta/Elev= 30
       0  845.77    87.6  802.42  154.76757.9996   187.2  722.92   195.2  694.72
   199.2  690.36  214.11690.8903  243.79692.7209   266.9  695.21   274.9  688.96
   290.8  668.71  303.14665.0394  332.82667.1921  362.49665.0608   378.4  663.74
   394.4  653.98  421.85652.6326   442.2  652.06   454.1  644.59   463.4   642.9
     474  642.56   478.4  642.94     490  644.87   513.9  656.55   601.5  662.22
   685.1  702.36   740.9  732.81   756.8  737.91   884.2  806.01  1011.6   865.4
#Mann= 10 ,-1 , 0
       0     .12       0  154.76     .05       0  214.11     .06       0
  243.79     .05       0  303.14    .016       0  332.82     .06       0
  362.49     .05       0  421.85     .12       0   463.4    .045       0
   478.4     .12       0
Bank Sta=463.4,478.4
XS Rating Curve= 0 ,0
Exp/Cntr=0.3,0.1

Type RM Length L Ch R = 1 ,6987.5  ,409.7,397.9,387.1
XS GIS Cut Line= 2
     1745025.563      443551.232      1745772.09      443841.163
#Sta/Elev= 30
       0  770.57   32.52748.8198    79.7  710.76    87.7  700.34    91.6  697.81
   95.78697.7389   107.6  701.04  177.36704.2003   195.2  699.62     243  664.97
  254.31663.7128     286664.9733  317.68 661.546   334.7  662.28   362.6  659.45
   386.5  647.55   402.4  642.06   410.4  640.74   418.4  641.63   446.2  671.58
   470.2  689.47     518  718.01   529.9  723.07   545.8  734.41   653.4  798.82
   685.3  814.59   697.3  823.01   709.2  826.54   749.1  848.84   800.8  881.28
#Mann= 9 ,-1 , 0
       0     .12       0   32.52     .05       0   95.78     .06       0
  177.36     .05       0  254.31    .016       0     286     .05       0
  317.68     .12       0   402.4    .045       0   418.4     .12       0
Bank Sta=402.4,418.4
XS Rating Curve= 0 ,0
Exp/Cntr=0.3,0.1

Type RM Length L Ch R = 1 ,6589.6  ,513.1,500,485.7
XS GIS Cut Line= 3
     1744893.403      444123.553     1745292.268      444062.189
      1745732.93      444015.109
#Sta/Elev= 30
       0  779.15   39.52 755.014    59.9  737.24    71.9  714.16   74.73712.3629
   143.8  715.68   159.8  720.42  164.38718.3366   203.8  684.32  224.15682.8444
   247.7  683.86  254.03681.0157  283.91662.1163   313.8662.9446  343.68660.7914
  373.56646.0432   396.1  638.01   411.1  637.78   423.5  639.98  438.52 648.986
  462.85 665.833   487.4   685.1   507.4  694.31   543.3  717.75   555.3  721.77
   639.1  781.32   671.1  800.49     727  825.88   782.8  841.11   846.7  870.85
#Mann= 14 ,-1 , 0
       0     .12       0   39.52     .05       0   74.73     .06       0
  164.38     .05       0  224.15     .06       0  254.03     .05       0
  283.91    .016       0   313.8     .06       0  343.68     .05       0
  373.56     .12       0   396.1    .045       0   411.1     .12       0
  438.52     .06       0  462.85     .12       0
Bank Sta=396.1,411.1
XS Rating Curve= 0 ,0
Exp/Cntr=0.3,0.1

Type RM Length L Ch R = 1 ,6089.6  ,474.6,475.2,475.9
XS GIS Cut Line= 3
     1745251.355      444750.359     1745555.246      444475.877
     1745859.137      444201.394
#Sta/Elev= 30
       0  823.44   18.75811.8396    43.7  787.45    47.7  774.04    51.7  757.15
    55.7  745.53    59.6     742   62.82742.4186     155  748.36  174.38736.9913
   242.5  689.89   278.3  662.28   286.2  658.75  293.78659.0006  333.58660.4843
   353.8  658.57  371.26649.7981   393.6  638.59   397.6   638.3   409.5   638.6
  415.32638.7268   437.3  639.18  452.98643.0852   612.3  712.72   624.2  714.69
     652  727.66   727.6  778.16   799.1  817.72     811   826.8     819  829.49
#Mann= 11 ,-1 , 0
       0     .12       0   18.75     .05       0   62.82     .06       0
  174.38     .05       0  293.78    .016       0  333.58     .06       0
  371.26     .05       0   393.6    .045       0   409.5     .05       0
  415.32     .06       0  452.98     .12       0
Bank Sta=393.6,409.5
XS Rating Curve= 0 ,0
Exp/Cntr=0.3,0.1

Type RM Length L Ch R = 1 ,5614.3  ,455.8,478.9,494.5
XS GIS Cut Line= 3
     1745359.311      444884.912     1745731.707      444916.162
     1746230.405      444486.909
#Sta/Elev= 30
       0  856.02   51.16835.2095    63.6  828.96    80.8804.4318    91.4  802.87
    95.4  794.86    99.4  769.82   103.4  753.35     167  756.09   178.9  773.93
   182.9  774.62   186.8  772.47  199.36738.4996     229 683.868   234.6  663.97
   238.5  657.61  258.64657.9602  288.28659.0688   314.1  660.26     330  684.23
   345.9   699.1   357.8  706.56   377.7  707.71   497.3  648.96   577.1  640.44
     609  643.55   632.9  635.95   648.9  636.31   676.8  642.39  1031.7  867.47
#Mann= 9 ,-1 , 0
       0     .12       0   51.16     .05       0    80.8     .06       0
  199.36     .05       0     229    .016       0  258.64     .06       0
  288.28     .12       0   632.9    .045       0   648.9     .12       0
Bank Sta=632.9,648.9
XS Rating Curve= 0 ,0
Exp/Cntr=0.3,0.1

Type RM Length L Ch R = 1 ,5135.4  ,635.5,655.5,682.2
XS GIS Cut Line= 3
     1745421.111      444991.237     1745921.258      445115.375
     1746311.721      445097.797
#Sta/Elev= 30
       0  755.01    63.9  757.51    67.9  759.86    75.9  780.71    79.9  784.43
   103.9  784.84  110.58780.9266   115.8  773.77   127.8  737.95   135.8  726.69
   151.8  692.85   163.8   660.2  171.44656.2584  201.87657.8768  232.31657.1102
   239.7  657.55   247.7  663.81   255.7  686.73   275.6  718.57   287.6  726.65
   307.6  727.76   335.6  714.86   403.5  693.01   451.4  668.17   487.4  635.49
   503.3  634.32   511.3   634.2   519.3  634.25   555.2  643.14   906.2  657.03
#Mann= 7 ,-1 , 0
       0     .06       0  110.58     .12       0  171.44    .016       0
  201.87     .06       0  232.31     .12       0   503.3    .045       0
   519.3     .12       0
#XS Ineff= 2 , 0
                          553.12          645.31
Permanent Ineff=
       F       F
Bank Sta=503.3,519.3
XS Rating Curve= 0 ,0
Exp/Cntr=0.3,0.1