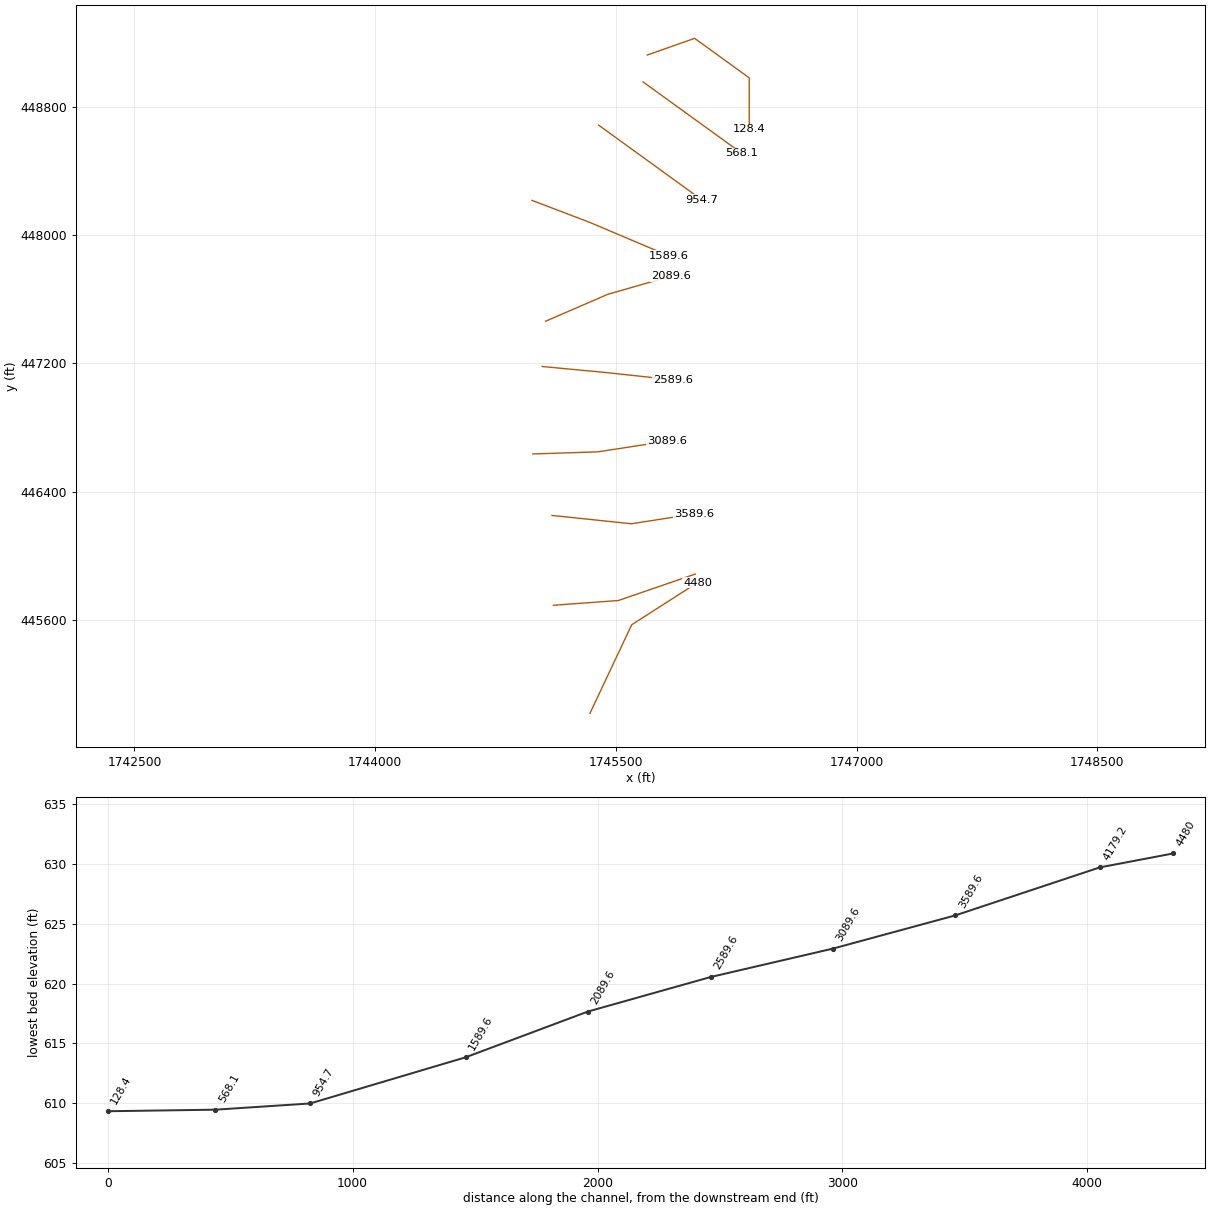
HEC-RAS study FORKCK.prj: FORKCK

--- FORKCK.g01 (geometry) --- (continued)

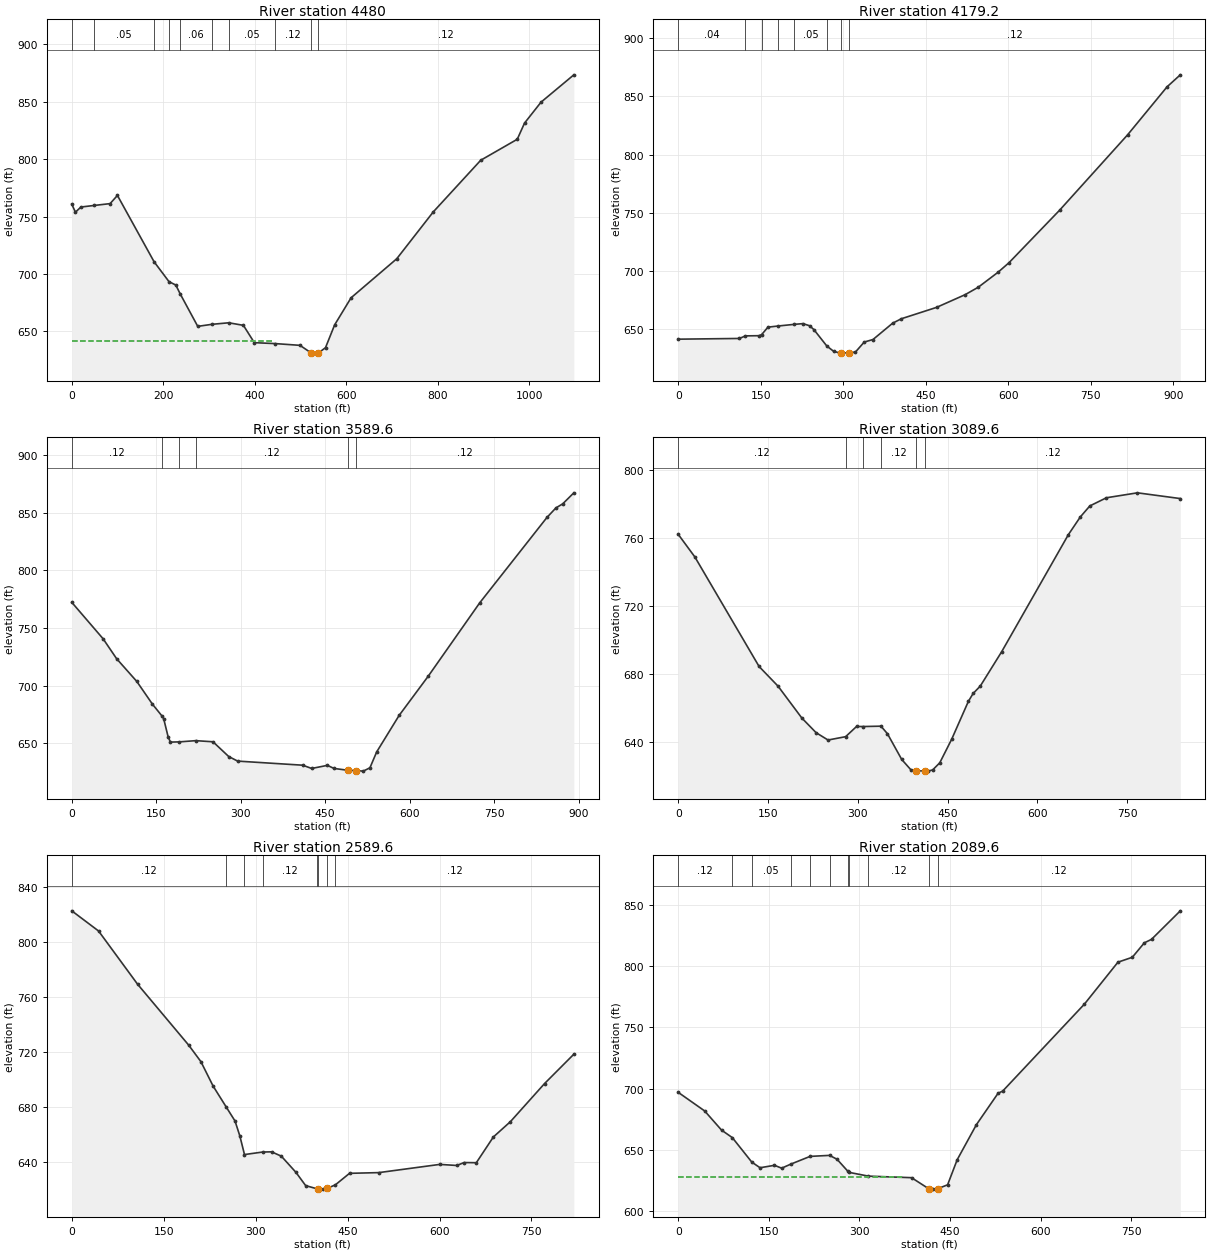
Type RM Length L Ch R = 1 ,4480    ,324.5,300.7,277.5
XS GIS Cut Line= 3
     1745338.714      445018.087      1745599.13      445570.387
     1746009.287      445832.974
#Sta/Elev= 30
       0  760.75       8  753.77      20  758.26    49.3759.6515    83.8  761.24
    99.8  768.38  179.92710.5596  212.57693.2036   227.5  690.22  237.09682.4949
   275.4  654.22  306.34655.9936  343.19657.3401   375.2  655.11   399.1     640
  444.84639.1892   498.9  637.67   522.6  631.26   537.6  630.93   538.8  630.88
   554.7  635.64   574.7  655.54   610.6  679.14   710.4  713.14   790.2  753.97
     894  799.04   973.9  817.35   989.8  831.45  1025.8  849.67  1097.6  873.53
#Mann= 10 ,-1 , 0
       0     .06       0    49.3     .05       0  179.92     .06       0
  212.57     .05       0  237.09     .06       0  306.34    .016       0
  343.19     .05       0  444.84     .12       0   522.6    .045       0
   537.6     .12       0
#XS Ineff= 2 , 0
          437.83  641.69
Permanent Ineff=
       F       F
Bank Sta=522.6,537.6
XS Rating Curve= 0 ,0
Exp/Cntr=0.3,0.1

Type RM Length L Ch R = 1 ,4179.2  ,594.4,589.6,590
XS GIS Cut Line= 3
     1745111.327      445691.857      1745515.84      445721.371
     1745995.007      445886.302
#Sta/Elev= 30
       0  641.68   111.3  642.29  122.07644.5017   147.1  644.66  151.69645.6499
     163  651.98   181.3  652.96  210.91654.3813   226.6  655.01   238.6  653.21
   246.5   649.9  270.14635.7449   282.3  631.32   294.2  629.71   295.2  629.72
   310.2     630   322.1  630.68     338   639.2   353.9  641.37   389.7  655.41
   405.6  659.21   469.4  668.93   521.3  679.82   545.2  686.21   581.2  699.07
   601.1  707.25   692.9  752.19   816.6   816.9   888.4  858.11   912.4  868.36
#Mann= 8 ,-1 , 0
       0     .04       0  122.07     .05       0  151.69     .06       0
   181.3      .1       0  210.91     .05       0  270.14     .12       0
   295.2    .045       0   310.2     .12       0
Bank Sta=295.2,310.2
XS Rating Curve= 0 ,0
Exp/Cntr=0.3,0.1

Type RM Length L Ch R = 1 ,3589.6  ,496.7,500,499.9
XS GIS Cut Line= 3
      1745102.55       446251.53     1745597.556      446199.746
     1745986.767      446260.562
#Sta/Elev= 30
       0  772.33    55.7  740.63    79.6  723.39   115.5   703.6   143.3  683.83
  160.93673.1617   163.2  671.27   171.2  655.31   175.2  650.92  190.63   651.1
  220.32652.1708   250.8  651.19   278.7  638.38   294.6  634.41   410.1  630.85
     426  628.02   453.9   630.7   465.8  628.02   490.2  626.46   505.2  626.12
   517.6   625.7   529.5  628.61   541.5  642.41   581.3  674.07     633  708.15
   724.5  771.92   843.9   846.1   859.8  854.36   871.8  857.87   891.6  867.45
#Mann= 6 ,-1 , 0
       0     .12       0  160.93     .06       0  190.63      .1       0
  220.32     .12       0   490.2    .045       0   505.2     .12       0
Bank Sta=490.2,505.2
XS Rating Curve= 0 ,0
Exp/Cntr=0.3,0.1

Type RM Length L Ch R = 1 ,3089.6  ,502.8,500,494.1
XS GIS Cut Line= 3
     1744983.079      446634.636      1745388.05      446647.893
     1745816.717      446713.796
#Sta/Elev= 30
       0   762.3    27.8  748.98   135.1  684.51   166.8  672.92   206.6  654.14
   230.4  645.54   250.3  641.23  279.67643.1992   297.9  649.19  309.23649.1714
  338.78649.3848   349.6  644.91   373.4   629.8   389.3  623.47   397.7  623.08
   412.7  622.99   417.1  622.92   425.1  623.62     437  627.83   456.9   641.7
   484.8  663.99   492.7  668.62   504.7  672.99   540.5  693.25   651.9  762.14
   671.8  772.53   687.7  779.02   715.5  783.84   767.3  786.74   838.9  783.36
#Mann= 6 ,-1 , 0
       0     .12       0  279.67     .06       0  309.23      .1       0
  338.78     .12       0   397.7    .045       0   412.7     .12       0
Bank Sta=397.7,412.7
XS Rating Curve= 0 ,0
Exp/Cntr=0.3,0.1

Type RM Length L Ch R = 1 ,2589.6  ,488.6,500,508.7
XS GIS Cut Line= 3
     1745041.114      447179.761      1745448.76      447141.199
     1745856.048       447096.86
#Sta/Elev= 30
       0  822.92    43.7  808.26   107.3   769.6   190.8  725.23   210.7  713.25
   230.6  695.49  252.14680.1672   266.4  670.05   274.3  659.11  281.81 645.679
  311.48647.5193     326  647.66   341.9  644.52   365.7  632.78   381.6  623.11
  400.48620.7272     402  620.74   409.5  620.54     417  621.11  430.17623.6829
   453.2  632.03     501  632.55   600.4  638.52   628.2  637.74   640.2  639.87
   660.1  639.75   687.9  658.47   715.7   669.6   771.4   697.3   819.2  718.66
#Mann= 8 ,-1 , 0
       0     .12       0  252.14     .06       0  281.81     .06       0
  311.48     .12       0  400.48    .016       0     402    .045       0
     417    .016       0  430.17     .12       0
Bank Sta=402,417
XS Rating Curve= 0 ,0
Exp/Cntr=0.3,0.1

Type RM Length L Ch R = 1 ,2089.6  ,517.4,500,484.5
XS GIS Cut Line= 3
     1745062.213      447461.725     1745449.744      447629.548
     1745843.083      447742.181
#Sta/Elev= 30
       0  696.85    43.8  681.63    71.7  665.97   89.62659.7885  121.81639.7764
   135.5  635.16   159.4  637.15   171.3  634.81  186.18638.0706  218.37644.4527
  250.55 645.277     263  642.11   280.5 632.502  282.74631.3988  314.92628.2938
   386.4  627.03   414.8  617.99   422.3  617.66   429.8  618.05   446.1  621.18
     462  641.73   493.8   670.4   529.6  696.04   537.5  697.97   672.6  769.02
   728.2  803.38     752  807.39   771.9  819.21   783.8  822.07   831.5  845.41
#Mann= 11 ,-1 , 0
       0     .12       0   89.62     .06       0  121.81     .05       0
  186.18     .06       0  218.37      .1       0  250.55     .06       0
   280.5     .12       0  282.74    .016       0  314.92     .12       0
   414.8    .045       0   429.8     .12       0
#XS Ineff= 2 , 0
          373.61  627.93
Permanent Ineff=
       F       F
Bank Sta=414.8,429.8
XS Rating Curve= 0 ,0
Exp/Cntr=0.3,0.1

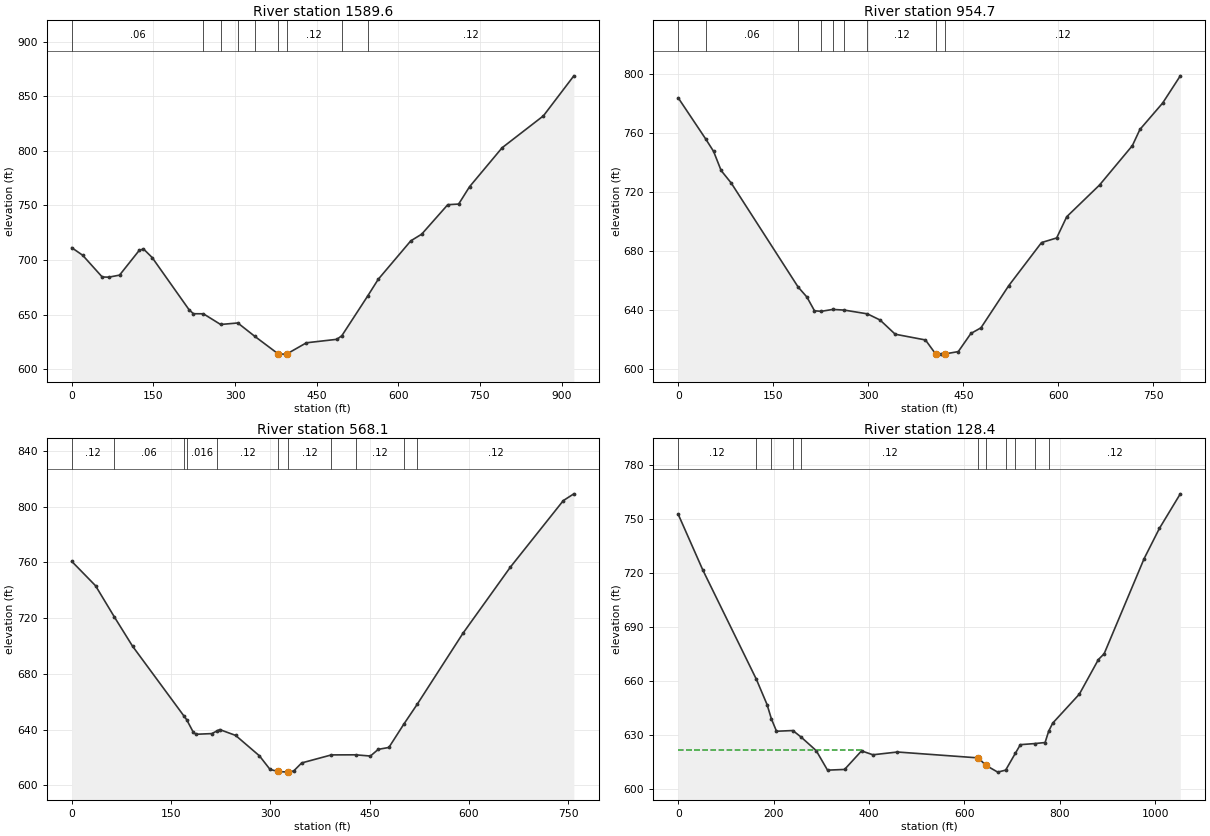
Type RM Length L Ch R = 1 ,1589.6  ,641.4,634.9,629.1
XS GIS Cut Line= 3
     1744977.473      448215.006     1745339.397       448077.13
     1745832.322      447868.339
#Sta/Elev= 30
       0   711.3      20  704.41    55.9  684.51    67.9  684.32    87.8  686.19
   123.8  708.76   131.8  710.16   147.7  702.32   215.6  654.45   223.6  650.84
  241.89650.7696   273.5 640.995  305.11642.3705  336.71629.9774   379.8  613.88
   391.3  613.83   394.8  613.88   431.2  624.22   487.2   627.4  496.34630.7443
  543.45666.8263   563.1  682.34     623  717.61     643  723.71   690.9   750.7
   710.9  751.28   730.9  767.13   790.8  802.86   866.7   832.1   922.6  868.74
#Mann= 9 ,-1 , 0
       0     .06       0  241.89     .05       0   273.5      .1       0
  305.11     .06       0  336.71     .12       0   379.8    .045       0
   394.8     .12       0  496.34    .016       0  543.45     .12       0
Bank Sta=379.8,394.8
XS Rating Curve= 0 ,0
Exp/Cntr=0.3,0.1

Type RM Length L Ch R = 1 ,954.7   ,386.4,386.6,386.7
XS GIS Cut Line= 2
     1745393.816      448683.306     1746035.743      448218.463
#Sta/Elev= 30
       0  783.69   43.38 755.814    55.8  747.42    67.7  734.46    83.6  725.99
  189.24655.4793   203.1  648.68   215.1  639.35  225.71638.9819  243.88640.2684
  262.18639.8212  298.64637.2722   318.6   633.1   342.5  623.47   390.3  619.57
   406.2  610.17   414.2  609.97   421.2  610.11   442.1  611.69     462  623.97
   477.9  627.81   521.7  656.35   573.5  685.59   597.4  688.73   613.3  703.12
   665.1  724.62   716.9  751.31   728.8  762.27   764.7  780.17   792.6  798.64
#Mann= 9 ,-1 , 0
       0     .12       0   43.38     .06       0  189.24     .05       0
  225.71     .06       0  243.88     .12       0  262.18    .016       0
  298.64     .12       0   406.2    .045       0   421.2     .12       0
Bank Sta=406.2,421.2
XS Rating Curve= 0 ,0
Exp/Cntr=0.3,0.1

Type RM Length L Ch R = 1 ,568.1   ,438.6,439.7,441.1
XS GIS Cut Line= 2
     1745669.906      448953.142     1746284.489      448508.697
#Sta/Elev= 30
       0  760.74    35.9  743.26   64.16720.9936    91.8  699.87  169.06649.9875
   173.5647.1447   183.6  638.06   187.6  636.63   211.6  637.11  219.47639.0719
   223.5     640   247.5  635.81   283.4  621.18   299.4  611.45   311.2609.9205
   326.2609.4858   327.3  609.45   335.3  610.33   347.3  616.05   392.2621.8125
  428.65621.8774   451.1     621     463  625.81     479  627.16  501.55643.8779
  521.88658.2208   590.8  709.06   662.6  756.66   742.5  804.38   758.4  809.23
#Mann= 11 ,-1 , 0
       0     .12       0   64.16     .06       0  169.06     .05       0
   173.5    .016       0  219.47     .12       0   311.2    .045       0
   326.2     .12       0   392.2    .016       0  428.65     .12       0
  501.55     .08       0  521.88     .12       0
Bank Sta=311.2,326.2
XS Rating Curve= 0 ,0
Exp/Cntr=0.3,0.1

Type RM Length L Ch R = 1 ,128.4   ,139.3,128.4,116.9
XS GIS Cut Line= 4
     1745696.164      449120.677     1745991.303      449224.843
     1746331.581      448978.315     1746331.581      448658.871
#Sta/Elev= 30
       0  752.68    51.5  721.74  163.86660.9106   186.2  646.91  195.19639.0344
     206  632.06  240.33632.4484  257.83628.7575   289.2   621.3     313  610.42
   348.7  610.81   384.3  621.13   408.1  618.97   459.6  620.51   629.4617.2274
   644.4 613.192   669.8  609.32  686.43 610.439  706.58619.7247   717.3   624.6
  747.11625.1913   769.1  625.78  776.64632.1014   785.1  636.58     841  652.72
   880.9  671.95   892.9  675.14   976.8   728.1  1008.7  744.83  1052.6  764.09
#Mann= 11 ,-1 , 0
       0     .12       0  163.86     .06       0  195.19    .016       0
  240.33      .1       0  257.83     .12       0   629.4    .045       0
   644.4     .12       0  686.43     .06       0  706.58    .016       0
  747.11     .06       0  776.64     .12       0
#XS Ineff= 2 , 0
          385.45  621.86
Permanent Ineff=
       F       F
Bank Sta=629.4,644.4
XS Rating Curve= 0 ,0
Exp/Cntr=0.3,0.1
LCMann Table=0

Chan Stop Cuts=-1
Use User Specified Reach Order=0
Composite Channel Slope=5